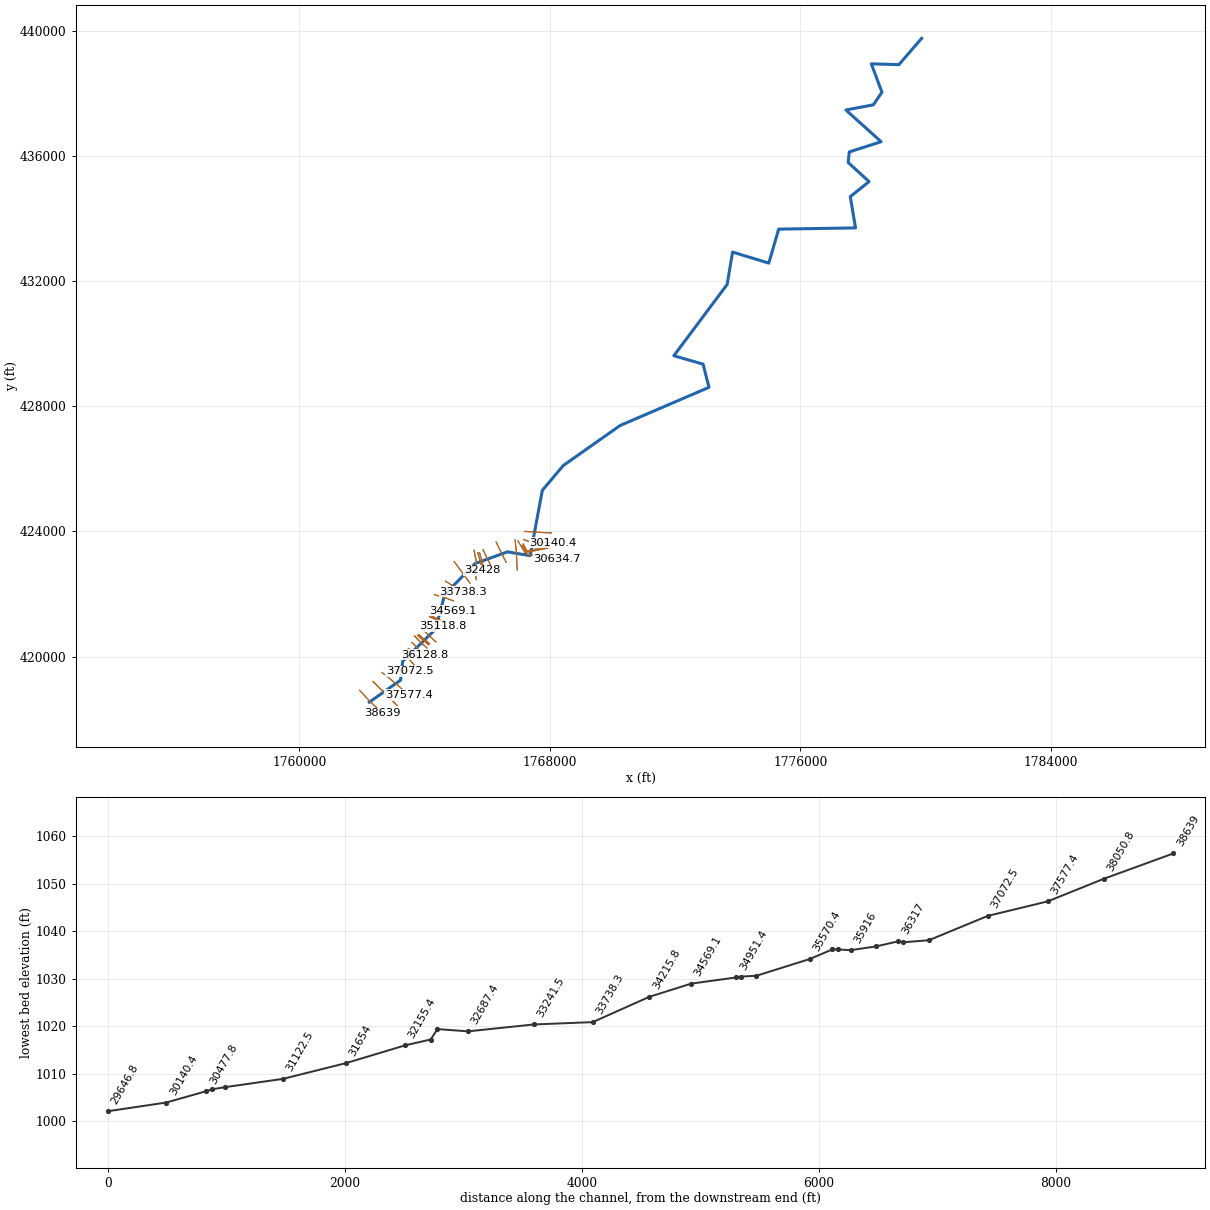
--- DaysRun.prj (project) ---

Proj Title=DaysRun
Current Plan=p01
Default Exp/Contr=0,0
English Units
Geom File=g01
Flow File=f01
Plan File=p01
BEGIN DESCRIPTION:
END DESCRIPTION:
DSS Export Rating Curves= 0
DSS Export Rating Curve Sorted= 0
DSS Export Volume Flow Curves= 0
DXF OffsetX= 0
DXF OffsetY= 0
DXF ScaleX= 0
DXF ScaleY= 0

--- DaysRun.p01 (plan) ---

Plan Title=Floodplain
Program Version=4.00
Geom File=g01
Flow File=f01
K Sum by GR=0
Std Step Tol=0.01
Critical Tol=0.01
Num of Std Step Trials=20
Max Error Tol=0.3
Flow Tol Ratio=0.001
Split Flow NTrial=30
Split Flow Tol=0.02
Split Flow Ratio=0.02
Log Output Level=0
Friction Slope Method=1
Unsteady Friction Slope Method=2
Unsteady Bridges Friction Slope Method=1
Global Log Level=0
CheckData=False
Run HTab=0
Run UNet=0
Run PostProcess=0
UNET Theta=0
UNET Theta Warmup=0
UNET ZTol=0
UNET ZSATol=0
UNET MxIter=0
UNET MaxInSteps=0
UNET DtIC=0
UNET DtMin=0
UNET MaxCRTS=0
UNET WFStab=0
UNET SFStab=0
UNET WFX=0
UNET SFX=0
UNET DSS MLevel=0
UNET DZMax Abort=0
UNET Convert EG Bridges=0
UNET Use Existing IB Tables=0
UNET Froude Limit=0
UNET Froude Power=0
Write IC File=0
Echo Input=False
Echo Output=False
Write Detailed=0

--- DaysRun.f01 (steady flow) ---

Flow Title=NFF Regression Equation
Program Version=4.10
Number of Profiles= 1
Profile Names=P100yr
River Rch & RM=DaysRun,Main            ,38639
     937
River Rch & RM=DaysRun,Main            ,35916
    1003
River Rch & RM=DaysRun,Main            ,34215.8
    1051
River Rch & RM=DaysRun,Main            ,32687.4
    1112
River Rch & RM=DaysRun,Main            ,32370.7
    1288
River Rch & RM=DaysRun,Main            ,30634.7
    1307
River Rch & RM=DaysRun,Main            ,30140.4
    1870
River Rch & RM=DaysRun,Main            ,28437.7
    1896
River Rch & RM=DaysRun,Main            ,28161.3
    2307
River Rch & RM=DaysRun,Main            ,24598.1
    2364
River Rch & RM=DaysRun,Main            ,24289.8
    2643
River Rch & RM=DaysRun,Main            ,21844.5
    2804
River Rch & RM=DaysRun,Main            ,16430.6
    2951
River Rch & RM=DaysRun,Main            ,12646.8
    3165
River Rch & RM=DaysRun,Main            ,5663.7
    3284
River Rch & RM=DaysRun,Main            ,1090.7
    3390
Boundary for River Rch & Prof#=DaysRun,Main            , 1
Up Type= 0
Dn Type= 3
Dn Slope=0.00259
DSS Import GetInterval= 0
DSS Import GetPeak= 0
DSS Import FillOption= 0

--- DaysRun.g01 (geometry) ---

Geom Title=USGS 10m DEM
Program Version=4.10

River Reach=DaysRun         ,Main
Reach XY= 30
     1762234.305      418541.769     1763232.498      419244.995
     1763300.581      419847.715     1764348.507      420872.742
      1764642.72      421979.348     1765605.884       422968.57
      1766644.85      423344.241     1767371.387      423224.162
     1767760.276      425310.968     1768426.943      426102.634
     1770243.513      427382.272     1773082.169      428602.646
     1772894.669      429343.618     1771959.773      429613.063
     1773662.898       431890.32     1773835.641      432925.563
     1774992.238      432572.264      1775308.21      433658.375
     1777761.509      433698.305     1777594.842      434697.611
     1778194.669      435177.125     1777527.829      435788.583
     1777561.683      436125.736     1778580.085      436451.952
     1777454.565      437466.187      1778330.78      437631.118
      1778605.78      438035.111      1778266.37      438941.535
     1779145.884      438914.625     1779873.295      439755.889

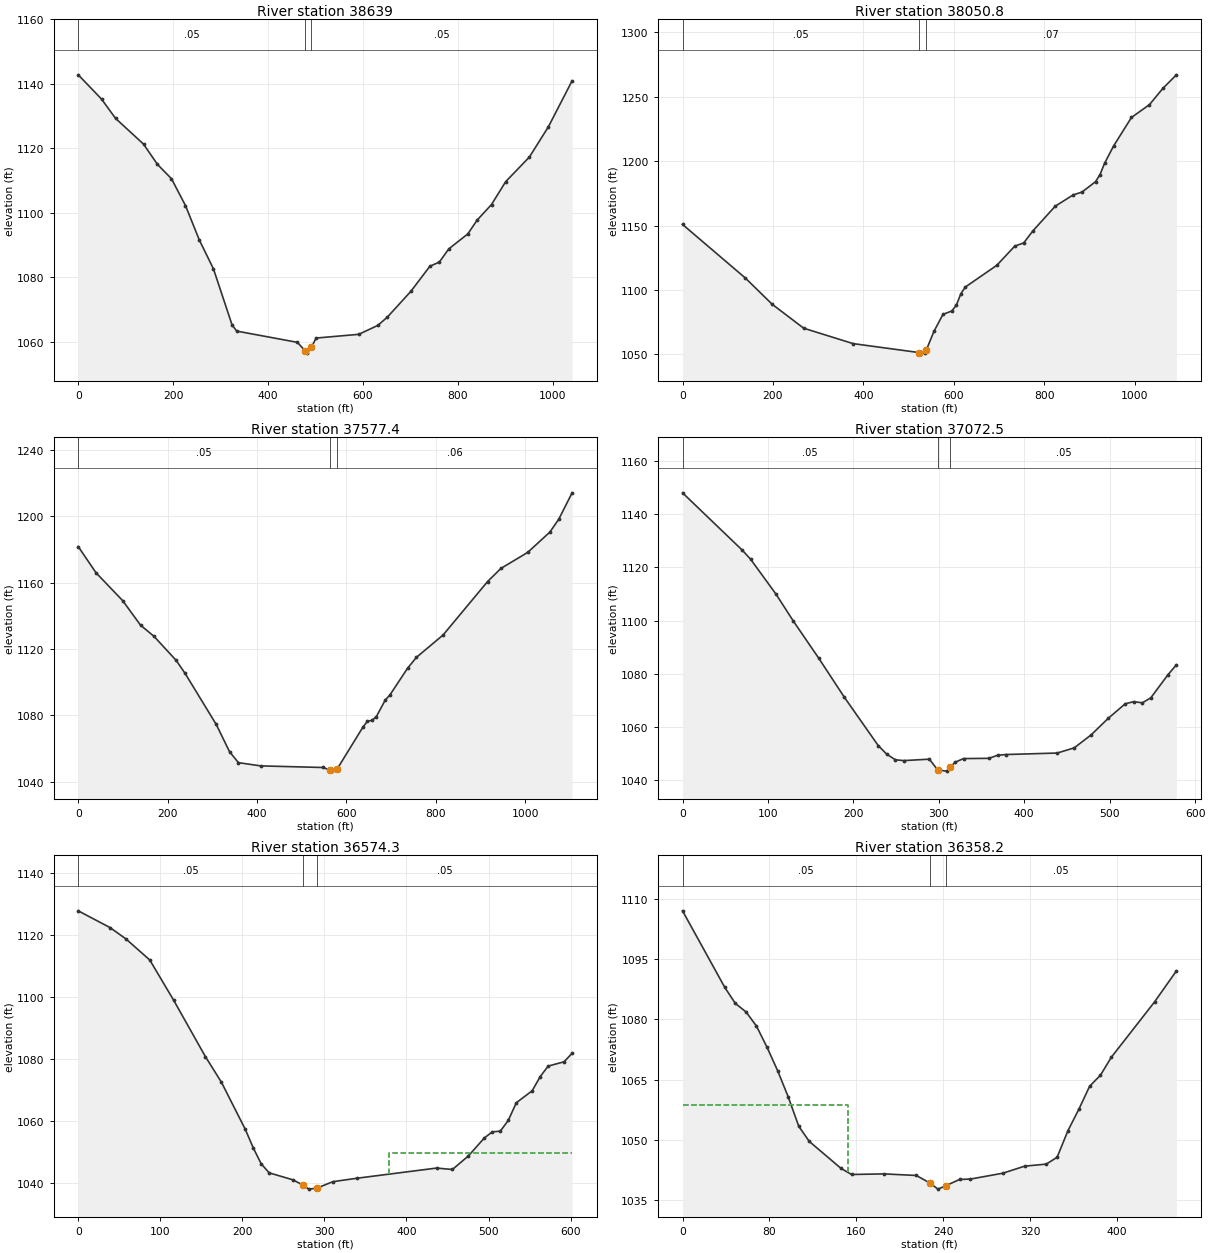
Type RM Length L Ch R = 1 ,38639   ,587.4,588.2,587.9
XS GIS Cut Line= 3
     1761927.882      418919.026     1762262.734      418559.217
      1762664.21      418183.783
#Sta/Elev= 30
       0  1142.8    49.2 1135.26    78.6 1129.29   137.6  1121.3   167.1 1114.98
   196.6 1110.54   226.1 1102.21   255.6 1091.42   285.1 1082.55   324.4 1065.12
   334.2 1063.23     462 1059.74   478.1 1057.18   481.7 1056.39   491.5  1058.2
   501.5 1061.07   591.5 1062.23   631.4 1064.98   651.4 1067.52   701.4 1075.59
   741.4 1083.37   761.4 1084.67   781.3 1088.77   821.3  1093.4   841.3 1097.74
   871.3 1102.53   901.3 1109.65   951.2 1117.28   991.2 1126.65  1041.2 1140.95
#Mann= 3 , 0 , 0
       0     .05       0   478.1    .045       0   491.5     .05       0
Bank Sta=478.1,491.5
XS Rating Curve= 0 ,0
Exp/Cntr=0.3,0.1

Type RM Length L Ch R = 1 ,38050.8 ,471.1,473.3,475
XS GIS Cut Line= 3
     1762353.585      419202.473     1762739.149      418815.882
     1763128.507      418433.073
#Sta/Elev= 30
       0 1150.87     139 1109.27   198.5 1088.86     268 1070.36   377.2 1058.42
   523.8 1051.44   526.1 1051.04   536.1 1051.29   538.8 1053.26   555.9 1067.88
   575.8 1081.08   595.6 1083.78   605.6 1088.37   615.5 1097.16   625.4 1102.34
   694.9 1119.16   734.6 1134.05   754.5 1136.56   774.3 1145.71     824 1164.99
   863.7 1173.77   883.5 1176.02   913.3 1184.08   923.2 1189.61   933.2  1198.3
     953 1211.66   992.7 1233.88  1032.4 1243.77  1062.2 1256.47    1092 1266.94
#Mann= 3 , 0 , 0
       0     .05       0   523.8    .045       0   538.8     .07       0
Bank Sta=523.8,538.8
XS Rating Curve= 0 ,0
Exp/Cntr=0.3,0.1

Type RM Length L Ch R = 1 ,37577.4 ,491.3,504.9,518.2
XS GIS Cut Line= 3
     1762648.916      419487.014     1763089.918      419129.781
     1763490.165      418771.457
#Sta/Elev= 30
       0 1181.76    39.8 1165.97    99.6 1149.09   139.4 1134.34   169.3 1127.66
     219 1113.13     239 1105.28   308.7 1074.46   338.5    1058   358.4 1051.39
   408.2 1049.44   547.6 1048.47   563.7 1046.87   567.5 1046.28   578.7 1047.31
   637.2 1072.97   647.1 1076.45   657.1 1076.88     667  1079.2   686.9 1089.21
   696.9  1092.1   736.7 1108.34   756.6 1114.94   816.2 1128.41   915.7 1160.66
   945.6 1168.59  1005.3 1178.22    1055 1190.48  1074.9 1198.23  1104.8  1214.2
#Mann= 3 , 0 , 0
       0     .05       0   563.7    .045       0   578.7     .06       0
Bank Sta=563.7,578.7
XS Rating Curve= 0 ,0
Exp/Cntr=0.3,0.1

Type RM Length L Ch R = 1 ,37072.5 ,513.5,498.2,482.1
XS GIS Cut Line= 3
     1762941.554      419606.526     1763177.665      419568.332
      1763514.47      419530.137
#Sta/Elev= 30
       0 1148.13    69.8 1126.56    79.7  1123.1   109.6 1109.86   129.6 1099.84
   159.4 1085.81   189.4 1071.09   229.2 1052.81   239.2 1049.58   249.2  1047.5
   259.1  1047.2     289 1047.74   298.6 1043.68     309 1043.23   313.6 1044.78
   318.9 1046.56   328.9 1047.96   358.8 1048.05   368.8 1049.22   378.8 1049.49
   438.6 1050.05   458.5    1052   478.4 1056.92   498.4 1063.16   518.3 1068.64
   528.3 1069.42   538.3 1068.98   548.2 1070.88   568.2 1079.55   578.1  1083.3
#Mann= 3 , 0 , 0
       0     .05       0   298.6    .045       0   313.6     .05       0
Bank Sta=298.6,313.6
XS Rating Curve= 0 ,0
Exp/Cntr=0.3,0.1

Type RM Length L Ch R = 1 ,36574.3 ,213.6,216.1,219
XS GIS Cut Line= 3
     1763257.526      420178.141     1763451.273      419974.588
     1763665.078      419735.432
#Sta/Elev= 30
       0 1127.85    38.8 1122.44    58.1  1118.8    87.2 1111.99   116.3 1099.01
     155 1080.82   174.4 1072.62   203.5 1057.42   213.2 1051.45   222.9 1046.29
   232.6 1043.36   261.6  1041.1   273.9  1039.4     281  1038.1   290.7  1038.4
   310.2  1040.5   339.3  1041.6   436.6 1044.89     456 1044.44   475.4  1048.8
   494.9 1054.61   504.6 1056.57   514.3 1056.79     524 1060.24   533.8 1065.95
   553.2 1069.83   562.9 1074.37   572.6 1077.77   592.1 1079.18   601.8 1081.92
#Mann= 3 , 0 , 0
       0     .05       0   273.9    .045       0   290.7     .05       0
#XS Ineff= 2 , 0
                           378.5         1049.69
Permanent Ineff=
       F       F
Bank Sta=273.9,290.7
XS Rating Curve= 0 ,0
Exp/Cntr=0.3,0.1

Type RM Length L Ch R = 1 ,36358.2 ,41.1,41.1,41.1
XS GIS Cut Line= 3
      1763464.21      420226.578     1763588.946      420118.078
     1763811.866       419933.61
#Sta/Elev= 30
       0 1107.09    38.9 1087.99    48.6    1084    58.4 1081.89    68.1 1078.34
    77.8 1073.05    87.5 1067.26    97.2 1060.76     107 1053.36   116.7 1049.57
   145.9 1042.85   155.6 1041.32   185.3 1041.47   215.2 1041.08   227.7 1039.21
   235.2 1037.67   242.7 1038.56   255.1 1040.08   265.1 1040.18     295 1041.65
     315  1043.4   334.9 1043.91   344.9 1045.62   354.9 1052.28   364.9 1057.59
   374.8 1063.33   384.8 1066.09   394.8 1070.57   434.7 1084.41   454.7  1092.1
#Mann= 3 , 0 , 0
       0     .05       0   227.7    .045       0   242.7     .05       0
#XS Ineff= 2 , 0
          152.17 1058.76
Permanent Ineff=
       F       F
Bank Sta=227.7,242.7
XS Rating Curve= 0 ,0
Exp/Cntr=0.3,0.1

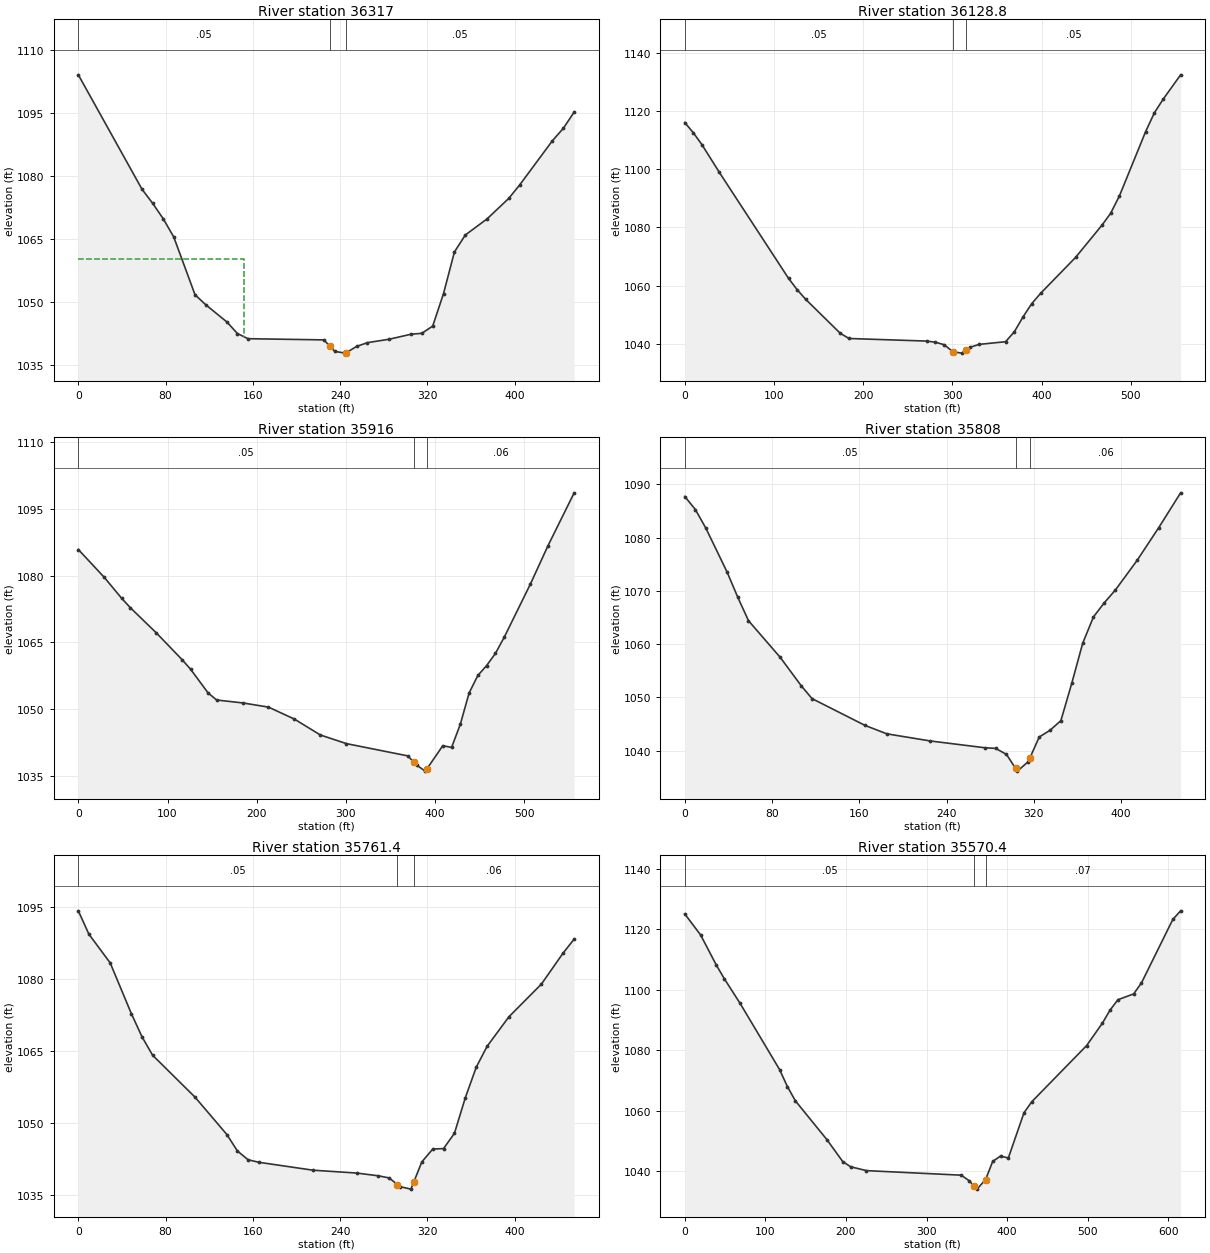
Type RM Length L Ch R = 1 ,36317   ,189,188.2,187.6
XS GIS Cut Line= 3
     1763495.807      420251.925     1763620.543      420143.425
     1763843.463      419958.957
#Sta/Elev= 30
       0 1104.04    58.4 1076.83    68.1 1073.51    77.8 1069.84    87.5 1065.49
     107 1051.76   116.7  1049.4   136.2 1045.29   145.9 1042.53   155.6  1041.3
   225.2 1041.02   230.4 1039.59   235.2 1038.27   245.1 1037.87   245.4 1037.92
   255.1 1039.45   265.1 1040.36     285 1041.17     305 1042.36     315 1042.58
     325 1044.31   334.9 1052.03   344.9 1061.93   354.9 1065.96   374.8 1069.78
   394.8 1074.68   404.8 1077.88   434.7 1088.35   444.7  1091.3   454.7 1095.18
#Mann= 3 , 0 , 0
       0     .05       0   230.4    .045       0   245.4     .05       0
#XS Ineff= 2 , 0
          152.17 1060.33
Permanent Ineff=
       F       F
Bank Sta=230.4,245.4
XS Rating Curve= 0 ,0
Exp/Cntr=0.3,0.1

Type RM Length L Ch R = 1 ,36128.8 ,212.8,212.8,212.7
XS GIS Cut Line= 3
     1763597.977       420448.54     1763791.724      420244.987
     1763999.019      420064.425
#Sta/Elev= 30
       0 1116.02     9.7 1112.46    19.4 1108.33    38.8 1098.87   116.3 1062.49
     126 1058.58   135.7 1055.23   174.4 1043.59   184.1 1041.83   271.3 1040.94
     281 1040.54   290.8 1039.69   300.7 1037.24   310.5  1036.8   315.7 1037.89
   320.3 1038.85   330.1 1039.81   359.6 1040.72   369.4  1044.1   379.2 1049.24
     389 1053.82   398.8  1057.3   438.1 1069.68   467.6 1080.72   477.4 1084.82
   487.2 1090.75   516.6 1112.85   526.5 1119.38   536.3 1124.03   555.9 1132.41
#Mann= 3 , 0 , 0
       0     .05       0   300.7    .045       0   315.7     .05       0
Bank Sta=300.7,315.7
XS Rating Curve= 0 ,0
Exp/Cntr=0.3,0.1

Type RM Length L Ch R = 1 ,35916   ,107.4,108.1,108.4
XS GIS Cut Line= 3
     1763677.231       420658.61     1763870.977      420455.057
     1764078.272      420274.495
#Sta/Elev= 30
       0  1085.9    29.1 1079.63    48.4 1074.96    58.1 1072.84    87.2 1067.18
   116.3 1061.11     126 1058.91   145.4 1053.64     155 1052.02   184.1 1051.37
   213.2 1050.42   242.3 1047.72   271.3 1044.15   300.6  1042.2   369.4 1039.44
   375.9 1038.07   379.2 1037.37     389 1036.01   390.9 1036.54   408.6 1041.73
   418.5 1041.35   428.3 1046.58   438.1 1053.59   447.9 1057.54   457.7 1059.76
   467.6  1062.5   477.4 1066.11   506.8 1078.11   526.5 1086.73   555.9 1098.66
#Mann= 3 , 0 , 0
       0     .05       0   375.9    .045       0   390.9     .06       0
Bank Sta=375.9,390.9
XS Rating Curve= 0 ,0
Exp/Cntr=0.3,0.1

Type RM Length L Ch R = 1 ,35808   ,46.5,46.6,46.6
XS GIS Cut Line= 3
     1763781.397      420670.328     1763906.134      420561.828
     1764129.054       420377.36
#Sta/Elev= 30
       0  1087.7     9.7 1085.25    19.4 1081.72    38.9 1073.47    48.6 1068.78
    58.4 1064.39    87.5 1057.51     107 1052.11   116.7 1049.76   165.3 1044.73
   185.3 1043.15   225.2 1041.81   275.1 1040.54     285 1040.42     295 1039.29
   303.4 1036.65     305 1036.15     315 1037.94   316.61038.679     325 1042.55
   334.9 1043.81   344.9 1045.63   354.9 1052.66   364.9 1060.16   374.8 1065.11
   384.8 1067.78   394.8 1070.13   414.8 1075.71   434.7 1081.88   454.7 1088.39
#Mann= 3 , 0 , 0
       0     .05       0   303.4    .045       0   316.6     .06       0
Bank Sta=303.4,316.6
XS Rating Curve= 0 ,0
Exp/Cntr=0.3,0.1

Type RM Length L Ch R = 1 ,35761.4 ,192.5,191,189.6
XS GIS Cut Line= 3
     1763813.515      420703.314     1763938.252      420594.814
     1764161.172      420410.346
#Sta/Elev= 30
       0 1094.26     9.7 1089.38    29.2  1083.4    48.6 1072.82    58.4 1067.97
    68.1 1064.13     107 1055.38   136.2 1047.58   145.9 1044.14   155.6 1042.32
   165.3 1041.79   215.2 1040.13   255.1 1039.54   275.1 1038.96     285 1038.52
   292.6 1037.14     295  1036.7     305 1036.18   307.6 1037.66     315 1041.86
     325 1044.54   334.9 1044.64   344.9 1047.82   354.9 1055.26   364.9 1061.62
   374.8 1065.96   394.8 1072.13   424.7 1078.98   444.7 1085.49   454.7 1088.36
#Mann= 3 , 0 , 0
       0     .05       0   292.6    .045       0   307.6     .06       0
Bank Sta=292.6,307.6
XS Rating Curve= 0 ,0
Exp/Cntr=0.3,0.1

Type RM Length L Ch R = 1 ,35570.4 ,439.7,451.6,463.3
XS GIS Cut Line= 3
      1763914.47      420891.248     1764177.111      420641.196
     1764361.085      420468.071
#Sta/Elev= 30
       0 1125.04    19.6 1118.11    39.2 1108.12      49 1103.66    68.6 1095.52
   117.6 1073.65   127.4 1067.98   137.2 1063.32   176.4 1050.48     196 1043.25
   205.8 1041.54   225.4 1040.26     343 1038.76   352.8 1036.95   359.4 1035.06
   362.6 1034.15  373.281037.308   382.1 1043.31   391.8 1045.07   401.5 1044.44
   420.9 1059.35   430.6 1063.02   498.7 1081.58   518.1 1088.92   527.8 1093.31
   537.5 1096.71     557 1098.63   566.7 1102.26   605.6 1123.23   615.3 1126.07
#Mann= 3 , 0 , 0
       0     .05       0   359.4    .045       0  373.28     .07       0
Bank Sta=359.4,373.28
XS Rating Curve= 0 ,0
Exp/Cntr=0.3,0.1

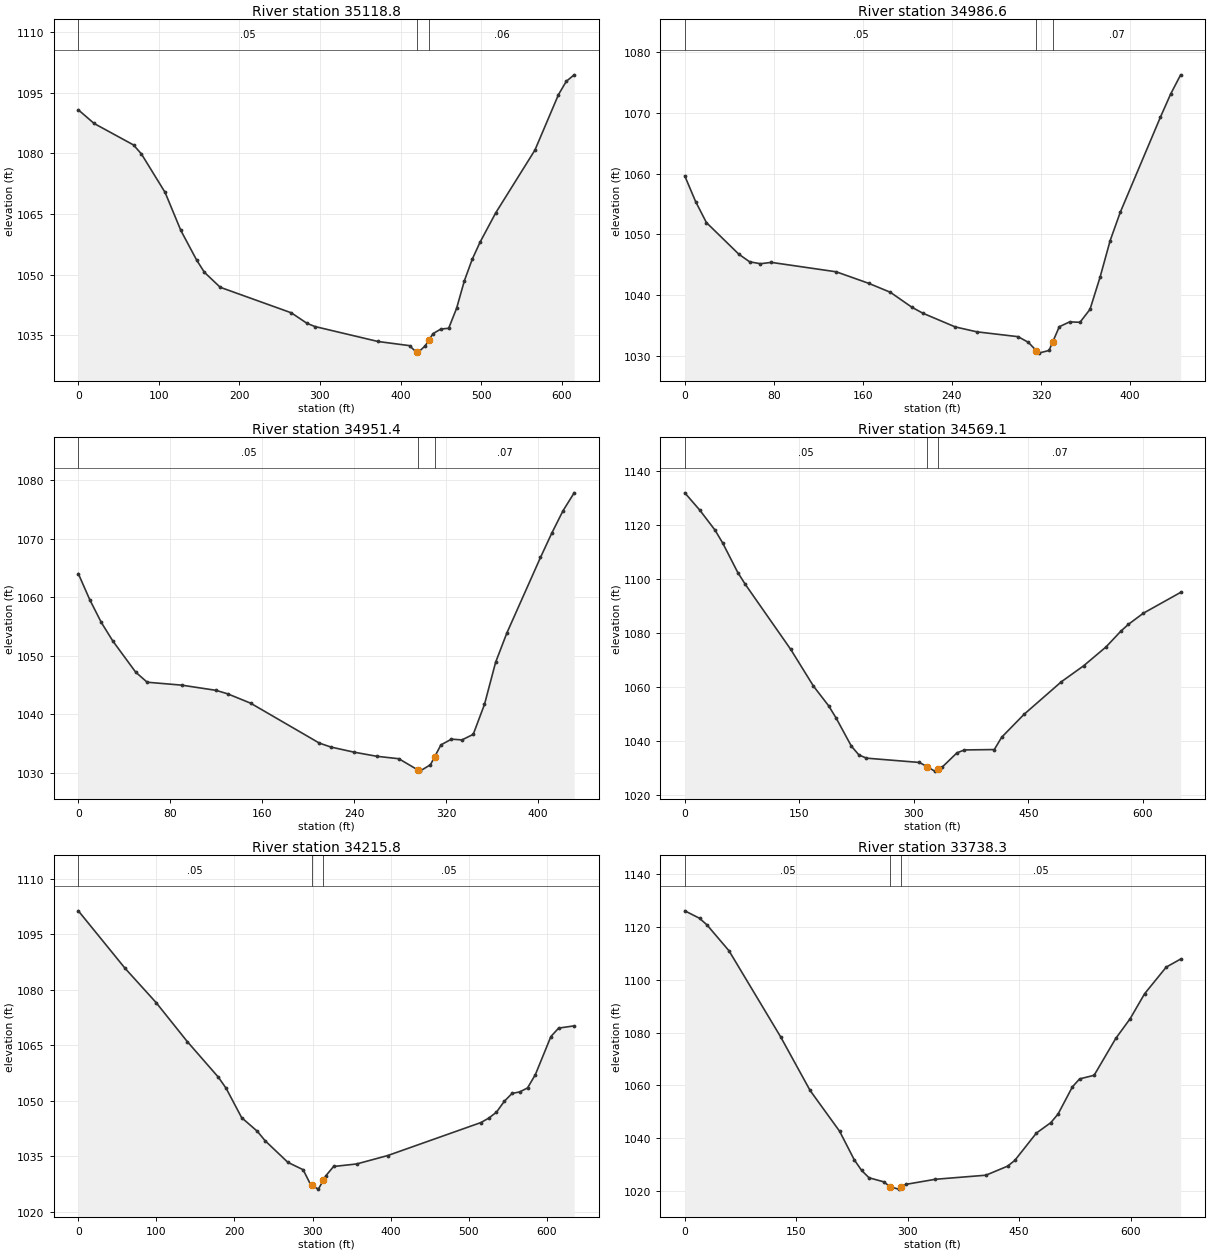
Type RM Length L Ch R = 1 ,35118.8 ,134.4,132.2,129.3
XS GIS Cut Line= 3
     1763999.106       421129.53     1764387.127      421026.665
      1764595.46      420977.186
#Sta/Elev= 30
       0 1090.77    19.6  1087.4    68.5 1082.09    78.3 1079.87   107.7 1070.36
   127.3 1060.94   146.9 1053.62   156.6 1050.58   176.2 1046.89   264.4 1040.58
   283.9 1037.98   293.7 1037.19     372 1033.49   411.2 1032.46  419.911030.799
   420.9 1030.61   430.6  1032.4  435.131033.804   440.4 1035.44   450.1 1036.56
   459.8 1036.76   469.6 1041.67   479.3 1048.51     489  1053.8   498.8 1058.06
   518.2 1065.29   566.9 1080.82   596.1 1094.52   605.8 1097.82   615.6 1099.43
#Mann= 3 , 0 , 0
       0     .05       0  419.91    .045       0  435.13     .06       0
Bank Sta=419.91,435.13
XS Rating Curve= 0 ,0
Exp/Cntr=0.3,0.1

Type RM Length L Ch R = 1 ,34986.6 ,36.9,35.2,33.5
XS GIS Cut Line= 4
      1764157.96      421272.759     1764397.543      421165.988
     1764484.783      421134.738     1764568.116      421099.582
#Sta/Elev= 30
       0 1059.63     9.7 1055.42    19.4 1051.95    48.6 1046.73    58.3 1045.48
      68 1045.17    77.7 1045.39     136 1043.84   165.2 1041.94   184.6 1040.47
     204    1038   213.7 1037.03   242.9 1034.76   262.3 1033.95   299.4 1033.15
   308.6 1032.22  315.751030.854   317.9 1030.44   327.2 1030.88  330.641032.345
   336.4 1034.79   345.7 1035.59     355 1035.52     364 1037.66     373 1042.93
   382.1 1048.98   391.1 1053.61   427.3 1069.34   436.4 1073.11   445.4 1076.29
#Mann= 3 , 0 , 0
       0     .05       0  315.75    .045       0  330.64     .07       0
Bank Sta=315.75,330.64
XS Rating Curve= 0 ,0
Exp/Cntr=0.3,0.1

Type RM Length L Ch R = 1 ,34951.4 ,378.8,382.4,386.4
XS GIS Cut Line= 4
     1764190.512      421311.821       1764432.7      421193.332
     1764491.293       421167.29     1764583.741       421136.04
#Sta/Elev= 30
       0 1064.05      10 1059.57      20  1055.7      30 1052.53    49.9  1047.2
    59.9 1045.48    89.9 1044.98   119.8 1044.09   129.8  1043.5   149.8  1041.9
   209.7 1035.06   219.7 1034.39   239.7 1033.52   259.6 1032.81   278.8 1032.39
  295.841030.414   297.1 1030.27   306.3 1031.36  309.831032.681   315.4 1034.76
   324.6 1035.74   333.7 1035.61   343.5 1036.56   353.3 1041.69     363  1048.9
   372.8 1053.92     402 1066.82   411.8 1070.97   421.6 1074.81   431.3 1077.88
#Mann= 3 , 0 , 0
       0     .05       0  295.84    .045       0  309.83     .07       0
Bank Sta=295.84,309.83
XS Rating Curve= 0 ,0
Exp/Cntr=0.3,0.1

Type RM Length L Ch R = 1 ,34569.1 ,354.6,353.2,351.3
XS GIS Cut Line= 3
     1764255.616       421629.53     1764571.888       421545.81
     1764884.522      421468.071
#Sta/Elev= 30
       0 1132.05    19.8 1125.58    39.7 1118.19    49.6 1113.47    69.4 1102.53
    79.3 1098.12   138.8 1074.02   168.5 1060.45   188.4 1053.15   198.3 1048.56
   218.1 1038.23     228 1034.96   237.9 1033.77   307.3 1032.17   317.1 1030.64
   327.2 1028.96   332.1 1029.69   336.9  1030.4   356.4 1035.74   366.2 1036.81
   405.3 1036.95     415 1041.53   444.3 1050.01   493.1 1062.06   522.4    1068
   551.7 1074.99   571.2 1080.86     581 1083.35   600.5 1087.46   649.3 1095.17
#Mann= 3 , 0 , 0
       0     .05       0   317.1    .045       0   332.1     .07       0
Bank Sta=317.1,332.1
XS Rating Curve= 0 ,0
Exp/Cntr=0.3,0.1

Type RM Length L Ch R = 1 ,34215.8 ,482,477.6,472.3
XS GIS Cut Line= 4
     1764317.029      421974.015     1764549.017      421916.073
     1764650.796      421882.074     1764920.111      421778.269
#Sta/Elev= 30
       0 1101.29    59.8 1085.79    99.6 1076.53   139.5 1066.01   179.3  1056.4
   189.3 1053.39   209.2 1045.46   229.2  1041.8   239.1 1039.27   268.4  1033.4
   287.9 1031.42   297.6 1027.35   298.8 1027.21   307.4 1026.18   313.8 1028.57
   317.2 1029.84   326.9 1032.29   356.4 1032.97   396.2 1035.24   515.6 1044.15
   525.6 1045.34   535.5 1046.95   545.5 1049.87   555.4    1052   565.4 1052.43
   575.3 1053.49   585.3 1057.08   605.2 1067.36   615.1 1069.64     635 1070.24
#Mann= 3 , 0 , 0
       0     .05       0   298.8    .045       0   313.8     .05       0
Bank Sta=298.8,313.8
XS Rating Curve= 0 ,0
Exp/Cntr=0.3,0.1

Type RM Length L Ch R = 1 ,33738.3 ,506,496.8,488
XS GIS Cut Line= 3
     1764664.468      422407.826      1764953.07      422233.439
     1765237.385      422065.812
#Sta/Elev= 30
       0 1125.97    19.8 1123.16    29.8 1120.67    59.5 1110.87   128.9  1078.4
   168.6 1058.12   208.3 1042.72   228.1  1031.9     238 1027.89   247.9 1025.14
   267.8  1023.6   276.2 1021.74   287.6 1020.85   291.2  1021.5   297.5 1022.65
   337.2 1024.57   405.2 1026.11   434.3 1029.52     444 1031.68   473.1 1042.02
   492.5 1045.96   502.2 1049.18   521.6 1059.49   531.3 1062.49   550.8 1063.85
   579.9 1077.77   599.3 1085.24   618.7 1094.64   647.8 1104.71   667.2 1107.75
#Mann= 3 , 0 , 0
       0     .05       0   276.2    .045       0   291.2     .05       0
Bank Sta=276.2,291.2
XS Rating Curve= 0 ,0
Exp/Cntr=0.3,0.1

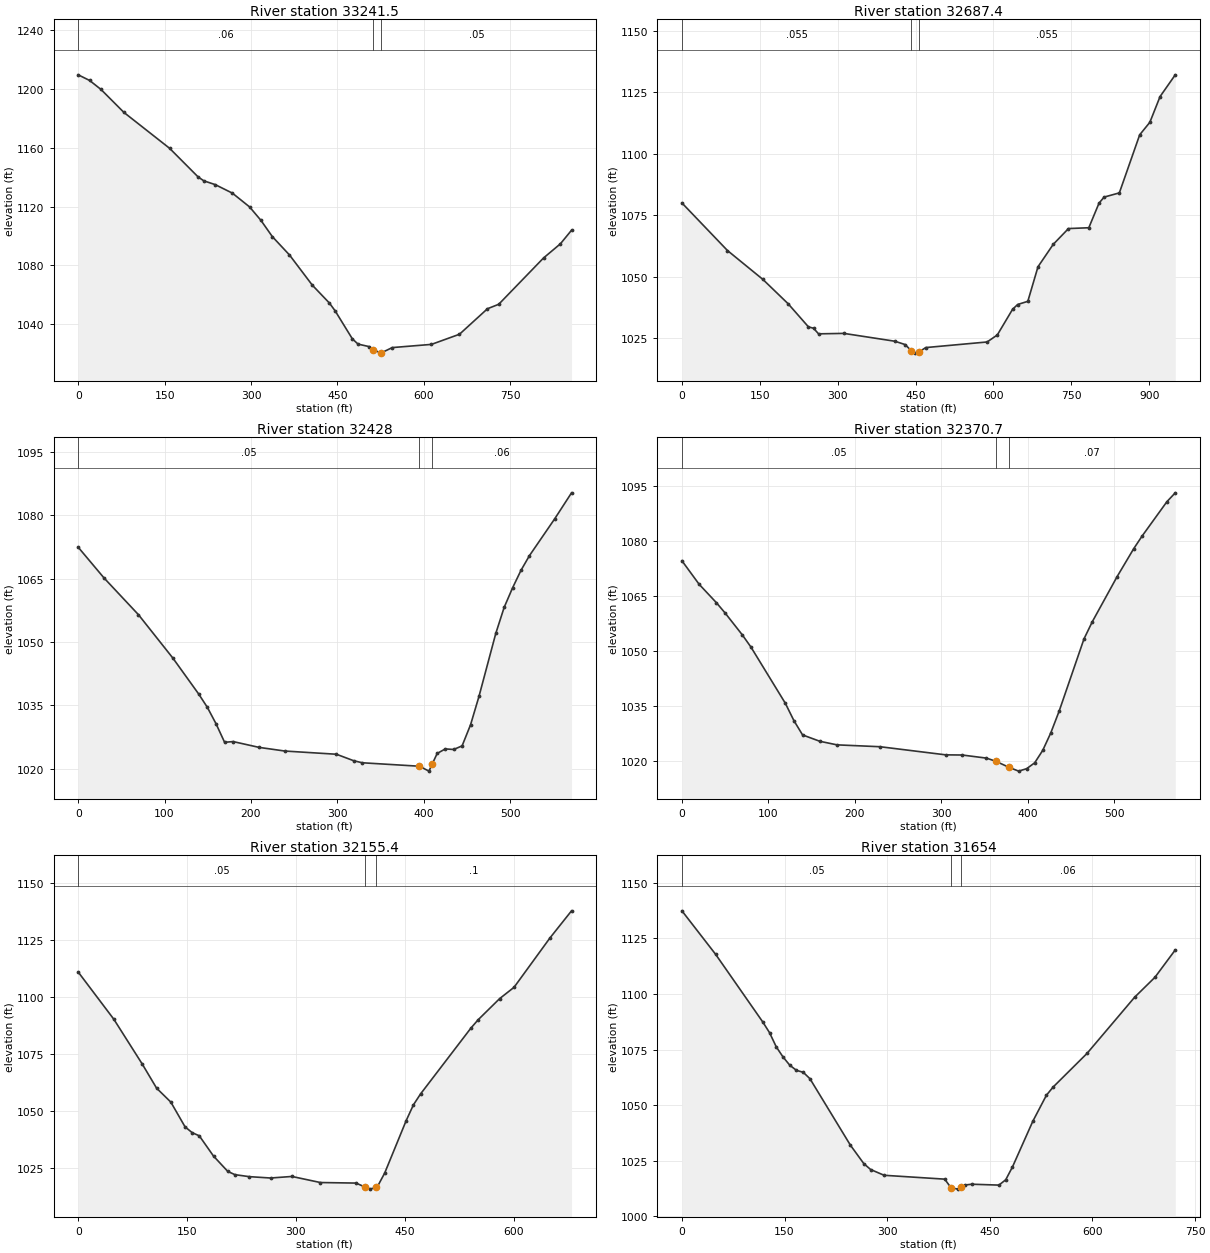
Type RM Length L Ch R = 1 ,33241.5 ,575.3,554.1,535.3
XS GIS Cut Line= 3
     1764945.382      423035.457      1765267.57      422595.718
     1765448.756      422342.722
#Sta/Elev= 30
       0 1209.71    19.8 1205.88    39.6 1199.74    79.3 1184.15   158.6 1159.73
   208.1 1140.25   218.1 1137.58   237.9    1135   267.6 1129.22   297.4 1119.86
   317.2 1110.68     337 1099.61   366.7 1087.16   406.4 1066.58   436.1  1054.4
     446 1049.11   475.8 1030.11   485.7  1026.5   505.5 1024.75   511.91022.826
   525.3 1020.36  526.221020.579   545.1 1024.13   613.2 1026.31   661.8 1033.21
   710.4 1050.57   729.9 1053.59   807.7  1085.1   836.9 1094.71   856.3 1103.98
#Mann= 3 , 0 , 0
       0     .06       0   511.9    .045       0  526.22     .05       0
Bank Sta=511.9,526.22
XS Rating Curve= 0 ,0
Exp/Cntr=0.3,0.1

Type RM Length L Ch R = 1 ,32687.4 ,251.1,259.4,263.9
XS GIS Cut Line= 4
     1765578.878      423395.456     1765651.578      423042.158
     1765605.874      422880.048     1765646.239      422460.777
#Sta/Elev= 30
       0 1080.03    87.7 1060.67     156  1048.9   204.7 1038.98   243.7  1029.6
   253.5 1029.03   263.2 1026.76     312 1026.94   410.2 1023.75     430 1022.39
     442 1019.87   449.9 1018.91     457 1019.45   469.7 1021.17   587.9 1023.45
   607.5  1026.3   636.9 1036.74   646.7  1038.7   666.3 1039.99   685.9 1054.06
   715.2 1063.17   744.6  1069.6   783.8 1069.94   803.4 1079.92   813.2 1082.41
   842.6 1084.12   881.8 1107.76   901.4 1112.86     921 1123.31   950.3 1132.17
#Mann= 3 , 0 , 0
       0    .055       0     442    .045       0     457    .055       0
Bank Sta=442,457
XS Rating Curve= 0 ,0
Exp/Cntr=0.3,0.1

Type RM Length L Ch R = 1 ,32428   ,61.4,57.3,53.3
XS GIS Cut Line= 5
      1765697.02      423314.944     1765769.937       423087.08
     1765801.187      422971.715     1765807.437      422905.743
     1765833.826      422761.993
#Sta/Elev= 30
       0 1072.42    29.9 1065.14    69.8 1056.43   109.6 1046.16   139.6 1037.62
   149.5  1034.5   159.5 1030.64   169.5 1026.21   179.4 1026.38   209.3 1025.01
   239.2 1024.14     299 1023.38   318.9 1021.85   328.9 1021.36   395.1 1020.54
   406.1 1019.38   410.1 1021.14   415.6 1023.56     425 1024.64   434.8 1024.51
   444.5 1025.37   454.3 1030.37     464 1037.06   483.5 1052.01   493.2 1058.18
     503 1062.83   512.7 1066.96   522.5 1070.44   551.7 1079.15   571.2 1085.31
#Mann= 3 , 0 , 0
       0     .05       0   395.1    .045       0   410.1     .06       0
Bank Sta=395.1,410.1
XS Rating Curve= 0 ,0
Exp/Cntr=0.3,0.1

Type RM Length L Ch R = 1 ,32370.7 ,201.5,215.3,228.8
XS GIS Cut Line= 5
     1765753.444      423314.944     1765826.361       423087.08
      1765854.92      422987.253     1765849.494      422903.703
     1765872.281      422761.559
#Sta/Elev= 30
       0 1074.61    19.9 1068.19    39.9 1063.16    49.8  1060.4    69.8  1054.4
    79.8 1051.07   119.6 1035.73   129.6 1030.96   139.6 1027.07   159.5 1025.34
   179.4 1024.36   229.3 1023.85   305.3 1021.63   324.2 1021.59   352.4 1020.74
   363.4 1019.86   378.4 1018.23   389.6 1017.19   398.9 1017.86   408.2 1019.47
   417.5 1022.87   426.8 1027.63   436.4 1033.53   465.2 1053.28   474.8 1057.96
   503.6 1070.31   522.8 1077.93   532.4 1081.34   561.2 1090.75   570.8 1093.15
#Mann= 3 , 0 , 0
       0     .05       0   363.4    .045       0   378.4     .07       0
Bank Sta=363.4,378.4
XS Rating Curve= 0 ,0
Exp/Cntr=0.3,0.1

Type RM Length L Ch R = 1 ,32155.4 ,501.4,501.4,501.1
XS GIS Cut Line= 3
     1765867.289      423413.034     1766044.036      423051.591
     1766165.466      422802.357
#Sta/Elev= 30
       0 1111.07    49.1 1090.38    88.3 1070.72     108 1060.19   127.6 1054.09
   147.2 1043.24     157  1040.7   166.8 1039.32   186.4 1030.44   206.1 1023.71
   215.9  1022.3   235.5 1021.43     265 1020.83   294.4 1021.51   333.6 1018.85
   382.7 1018.61   394.8 1016.92   402.3 1015.96   409.8 1016.79   412.2 1017.05
   422.2    1023   451.8 1045.97   461.8 1052.89   471.6 1057.66     541 1086.52
   550.9 1090.15   580.6 1099.44   600.4 1104.38   649.9 1126.02   679.6 1137.89
#Mann= 3 , 0 , 0
       0     .05       0   394.8    .045       0   409.8      .1       0
Bank Sta=394.8,409.8
XS Rating Curve= 0 ,0
Exp/Cntr=0.3,0.1

Type RM Length L Ch R = 1 ,31654   ,530.2,531.4,521.1
XS GIS Cut Line= 3
     1766283.956       423660.43     1766458.115      423296.112
     1766604.269      423014.597
#Sta/Elev= 30
       0 1137.42    49.2 1117.87   118.2 1087.39     128 1082.62   137.9  1076.2
   147.7 1071.69   157.6 1067.96   167.4 1065.64   177.3 1064.77   187.1 1061.88
   246.2 1031.99   265.9 1023.65   275.8 1021.02   295.5 1018.43   384.1 1016.69
   393.4 1012.75   403.8  1012.2   408.4 1013.06   413.7 1014.05   423.6 1014.41
   463.3 1014.01   473.2  1016.4   483.1 1022.19   512.8 1042.72   532.7 1054.45
   542.6 1058.16   592.1 1073.28   661.5  1098.5   691.3 1107.51     721 1119.82
#Mann= 3 , 0 , 0
       0     .05       0   393.4    .045       0   408.4     .06       0
Bank Sta=393.4,408.4
XS Rating Curve= 0 ,0
Exp/Cntr=0.3,0.1

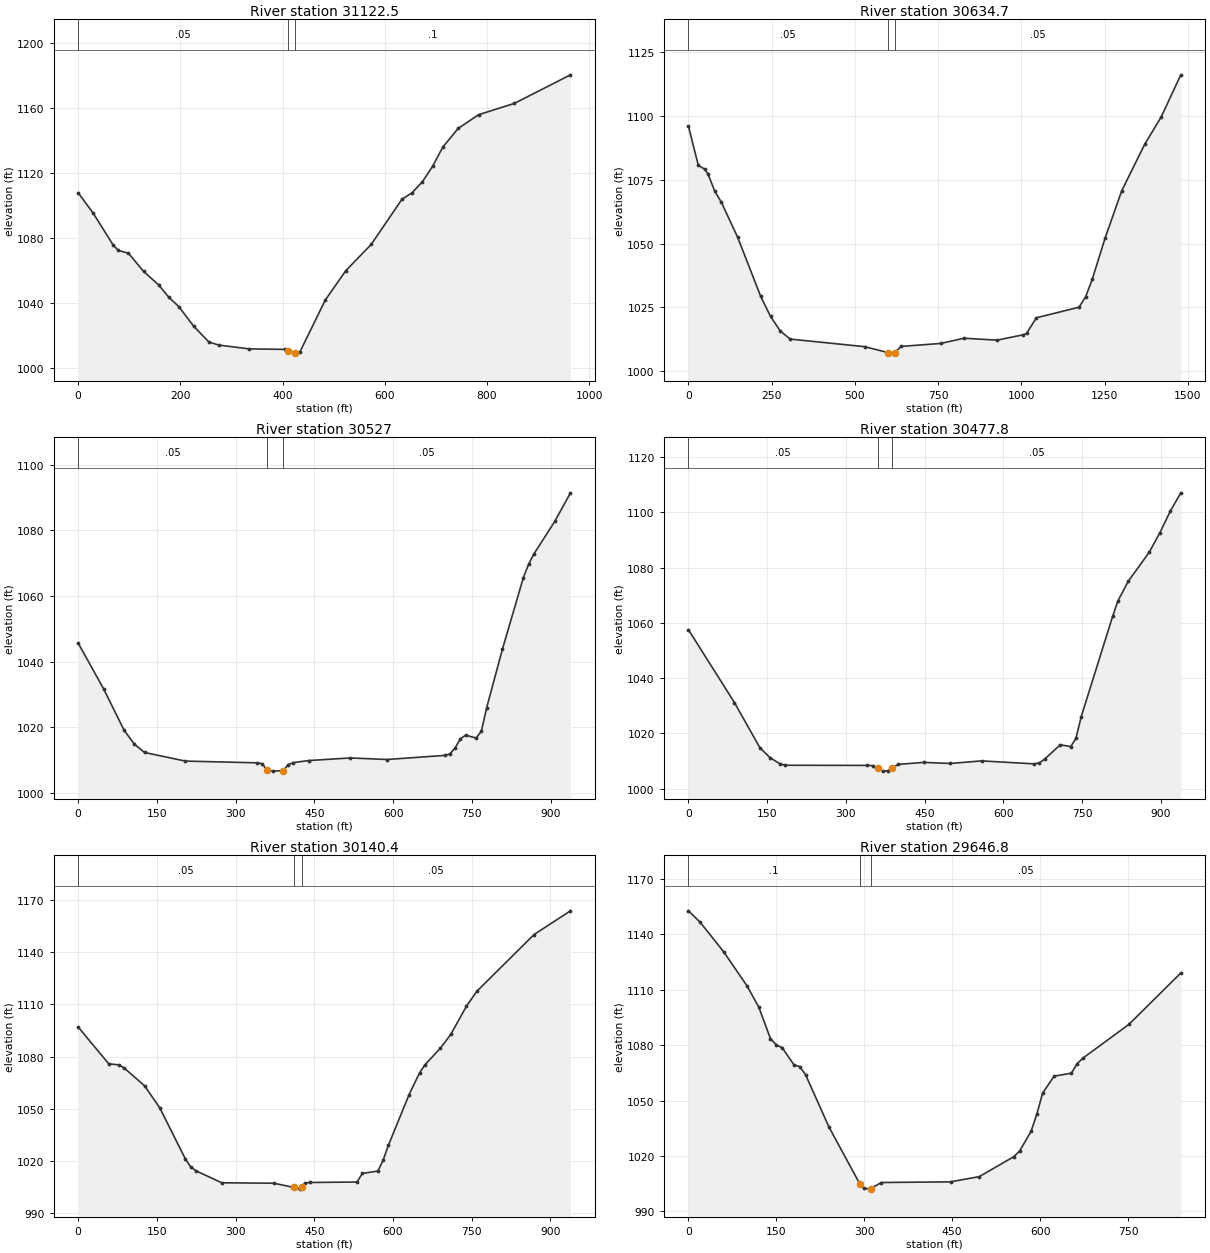
Type RM Length L Ch R = 1 ,31122.5 ,460.1,487.9,522
XS GIS Cut Line= 3
     1766892.029      423728.139     1766931.091      423336.212
     1766958.001      422766.984
#Sta/Elev= 30
       0 1107.62    29.5 1095.02    68.9 1075.25    78.8  1072.1    98.5 1070.39
     128 1059.21   157.6 1050.87   177.2 1043.37   196.9 1037.56   226.5  1025.3
     256 1015.73   275.7 1013.82   334.8  1011.5   403.9  1011.2   409.8 1010.09
   423.9 1008.89   424.8 1008.95   433.9 1009.54   483.8 1041.61   523.8  1059.6
   573.8 1075.88   633.8 1103.61   653.8 1107.66   673.8 1114.38   693.8 1123.93
   713.8 1135.73   743.8  1147.2   783.8 1155.67   853.8 1162.61   963.7 1180.21
#Mann= 3 , 0 , 0
       0     .05       0   409.8    .045       0   424.8      .1       0
Bank Sta=409.8,424.8
XS Rating Curve= 0 ,0
Exp/Cntr=0.3,0.1

Type RM Length L Ch R = 1 ,30634.7 ,95.8,107.7,118.4
XS GIS Cut Line= 5
     1766983.609      423691.029     1767207.567      423319.501
     1767294.373      423260.474     1767601.664      423229.224
     1768223.192      423119.849
#Sta/Elev= 30
       0 1095.85    29.6  1080.6    49.3 1079.06    59.2 1077.06    78.9 1070.52
    98.6  1066.2   147.9 1052.41   216.9 1029.37   246.5 1021.49   276.1 1015.76
   305.6 1012.64   529.2 1009.68   598.6 1007.39   608.5 1007.15  619.811007.362
   638.4 1009.77     758 1010.94   827.7 1012.99   926.5 1012.22  1005.4 1014.33
  1015.3 1014.83  1044.9 1020.98  1173.1 1025.11  1192.8 1029.14  1212.5 1035.95
  1251.9 1052.35  1301.2 1070.64  1370.3 1088.83  1419.6 1099.47  1478.7    1116
#Mann= 3 , 0 , 0
       0     .05       0   598.6    .045       0  619.81     .05       0
Bank Sta=598.6,619.81
XS Rating Curve= 0 ,0
Exp/Cntr=0.3,0.1

Type RM Length L Ch R = 1 ,30527   ,52.3,49.2,47.2
XS GIS Cut Line= 5
     1767127.706      423550.404     1767240.553      423335.126
     1767337.775      423345.543     1767462.775      423371.585
     1767922.845      423463.599
#Sta/Elev= 30
       0  1045.7    48.6 1031.73    87.5 1019.14     107 1014.93   126.4 1012.38
   204.2 1009.76   340.8 1009.23   350.7 1008.95  359.811006.914   370.3  1006.7
  390.81 1006.86   399.8 1008.64   409.6 1009.29   439.1 1009.92   518.4 1010.72
   588.3 1010.24   698.1 1011.49   708.1 1011.95   718.1 1013.79   728.1 1016.58
     738 1017.64     758 1016.78     768 1018.86     778 1025.99   807.9 1043.74
   847.9 1065.61   857.8 1069.65   867.8 1072.78   907.8 1082.76   937.7 1091.45
#Mann= 3 , 0 , 0
       0     .05       0  359.81    .045       0  390.81     .05       0
Bank Sta=359.81,390.81
XS Rating Curve= 0 ,0
Exp/Cntr=0.3,0.1

Type RM Length L Ch R = 1 ,30477.8 ,344.2,337.4,329.3
XS GIS Cut Line= 5
     1767148.539      423595.543     1767261.387      423380.265
     1767358.609      423390.682     1767483.609      423416.724
     1767943.678      423508.738
#Sta/Elev= 30
       0 1057.51    87.5 1031.16   136.1 1014.77   155.6 1011.14     175 1008.89
   184.7 1008.44   340.8 1008.38   350.7 1008.32   360.5 1007.41   370.3 1006.31
   380.1 1006.47   387.6  1007.5   399.8 1008.76   448.9 1009.48   498.5 1009.08
   558.4 1010.02   658.2 1008.94   668.2  1009.3   678.2 1010.62   708.1 1015.86
   728.1 1015.19     738 1018.19     748 1026.01   807.9 1062.37   817.9 1067.95
   837.9 1075.14   877.8 1085.66   897.8 1092.64   917.7 1100.47   937.7  1107.1
#Mann= 3 , 0 , 0
       0     .05       0   360.5    .045       0   387.6     .05       0
Bank Sta=360.5,387.6
XS Rating Curve= 0 ,0
Exp/Cntr=0.3,0.1

Type RM Length L Ch R = 1 ,30140.4 ,493.8,493.6,490.2
XS GIS Cut Line= 3
     1767167.637      423736.168     1767369.025      423663.251
      1768092.56      423631.994
#Sta/Elev= 30
       0 1096.95    58.4 1075.78    77.9 1075.21    87.6 1073.44   126.6 1063.23
   155.8 1050.41   204.4 1021.22   214.2 1016.83   224.1  1014.5   273.7 1007.56
   372.9 1007.31   410.7 1004.92   422.5 1003.92   425.7 1005.06   432.4 1007.44
   442.4 1007.73   531.6    1008   541.6 1012.91   571.3  1014.3   581.2  1020.5
   591.2 1028.97   630.8  1058.2   650.7 1070.63   660.6 1075.14   690.4 1084.78
   710.2 1092.67     740 1108.83   759.8 1117.42     869    1150   938.4  1163.6
#Mann= 3 , 0 , 0
       0     .05       0   410.7    .045       0   425.7     .05       0
Bank Sta=410.7,425.7
XS Rating Curve= 0 ,0
Exp/Cntr=0.3,0.1

Type RM Length L Ch R = 1 ,29646.8 ,500.5,500,499.7
XS GIS Cut Line= 3
     1767205.831      423998.321     1767504.898      423977.649
     1768044.373       423949.71
#Sta/Elev= 30
       0 1152.73      20 1146.52      60  1130.6    99.9  1112.1   119.9 1100.68
   139.9 1083.53   149.9 1080.14   159.9 1078.65   179.9 1069.44   189.9 1068.37
   199.8 1064.02   239.8 1035.65   292.3 1004.94   299.8 1002.61   309.6 1002.08
  310.77 1002.39   329.2 1005.66   447.1 1006.02   496.2 1008.84   555.2 1019.67
     565 1022.72   584.6 1033.42   594.4 1042.72   604.3 1054.08   623.9 1063.24
   653.4 1064.85   663.2 1070.01     673 1072.99   751.6 1091.29     840 1119.08
#Mann= 3 , 0 , 0
       0      .1       0   292.3    .045       0  310.77     .05       0
Bank Sta=292.3,310.77
XS Rating Curve= 0 ,0
Exp/Cntr=0.3,0.1