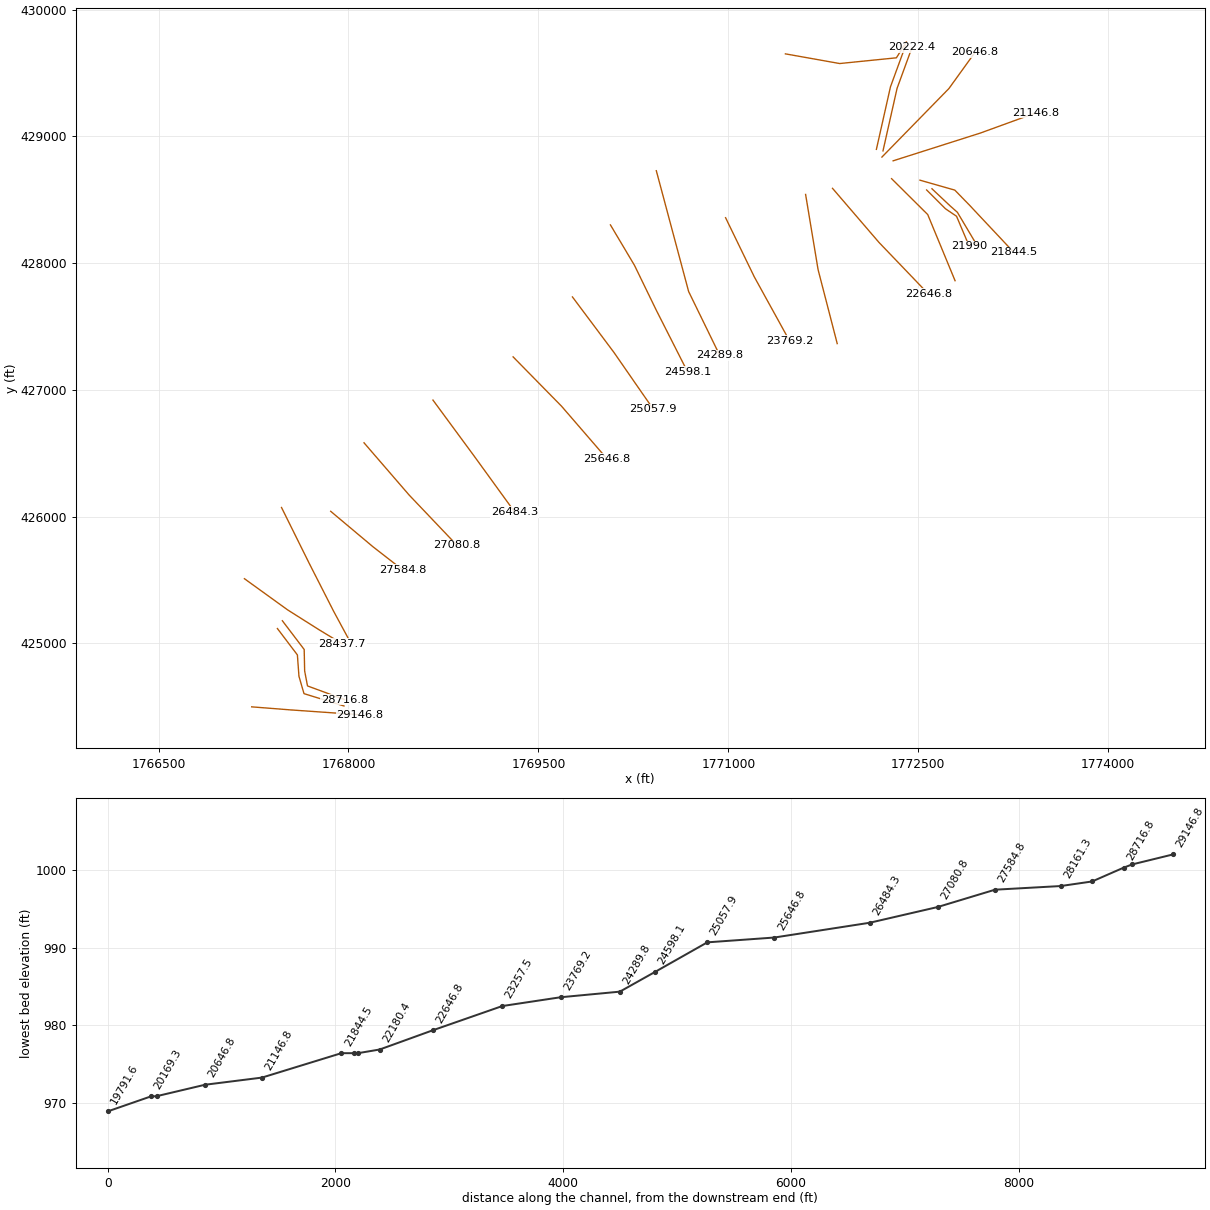
HEC-RAS study DaysRun.prj: DaysRun

--- DaysRun.g01 (geometry) --- (continued)

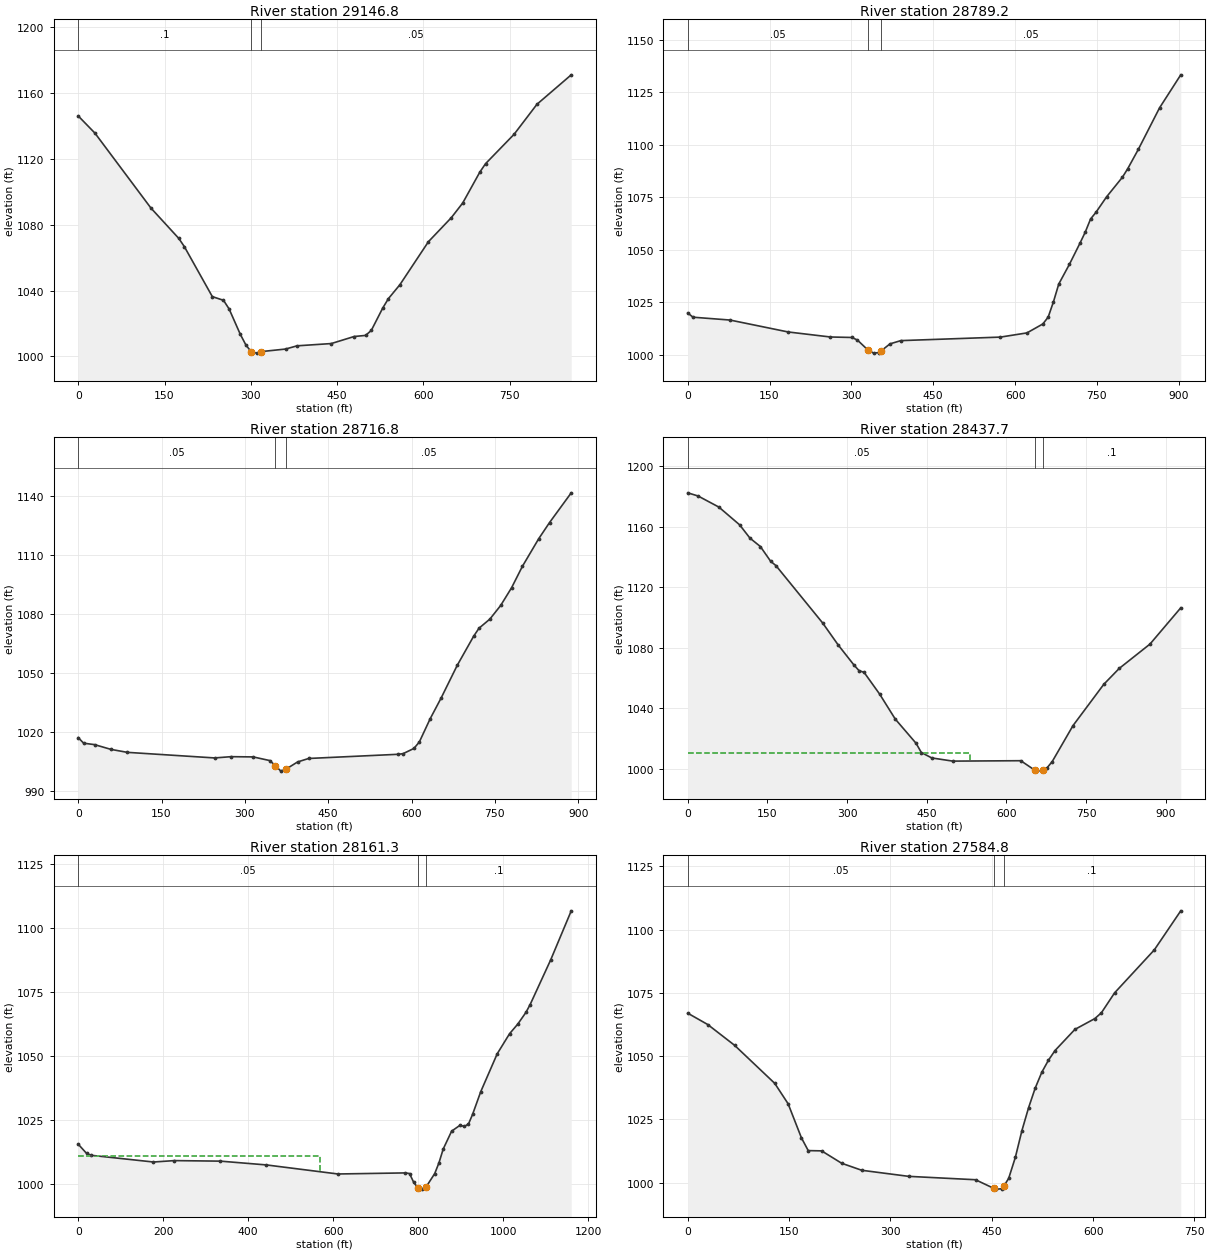
Type RM Length L Ch R = 1 ,29146.8 ,402.1,357.6,308.7
XS GIS Cut Line= 3
     1767235.345      424498.321     1767545.194      424474.068
      1768089.87      424436.067
#Sta/Elev= 30
       0 1146.22    29.1 1135.76   126.3 1090.24   174.8 1071.74   184.5 1066.73
   233.1 1036.34   252.5  1034.1   262.2 1028.88   281.7 1013.43   291.4 1006.95
   301.1 1002.62   310.8 1001.98   318.3 1002.92   360.4 1004.46   380.3 1006.42
   439.8  1007.8   479.6 1012.09   499.4 1012.75   509.3 1015.76   529.2 1029.38
   539.1 1035.13     559 1043.56   608.6 1069.73   648.3 1084.31   668.2 1093.27
     698 1112.08   707.9 1117.18   757.5 1135.06   797.2 1153.29   856.8 1171.21
#Mann= 3 , 0 , 0
       0      .1       0   301.1    .045       0   318.3     .05       0
Bank Sta=301.1,318.3
XS Rating Curve= 0 ,0
Exp/Cntr=0.3,0.1

Type RM Length L Ch R = 1 ,28789.2 ,64.5,72.4,83.7
XS GIS Cut Line= 5
      1767438.47      425116.376     1767596.456      424908.043
     1767608.609       424739.64     1767648.539      424602.488
     1767964.512      424505.265
#Sta/Elev= 30
       0 1019.86     9.7 1017.82    77.5 1016.47     184 1010.79   261.5 1008.39
   301.2 1008.16   311.1 1006.91     331 1002.02   340.9  1000.7   350.8 1000.99
   353.6 1001.56   370.7 1005.11   390.6 1006.66   573.2 1008.34   621.8 1010.34
   650.9  1014.6   660.7 1017.87   670.4  1025.2   680.1 1033.64   699.6 1043.02
     719 1053.12   728.7 1058.41   738.4 1064.64   748.2 1067.79   767.6 1075.14
   796.8 1084.55   806.5  1088.6     826 1097.85   864.8 1117.59   903.7 1133.34
#Mann= 3 , 0 , 0
       0     .05       0     331    .045       0   353.6     .05       0
Bank Sta=331,353.6
XS Rating Curve= 0 ,0
Exp/Cntr=0.3,0.1

Type RM Length L Ch R = 1 ,28716.8 ,253.9,279.2,304.3
XS GIS Cut Line= 5
     1767477.532      425177.791     1767650.058      424951.012
     1767653.748      424781.307     1767676.317      424663.251
      1767969.72      424555.613
#Sta/Elev= 30
       0 1017.34     9.8 1014.49    29.5 1013.76      59 1011.34    88.4 1009.84
   245.6    1007   275.1 1007.64   314.9 1007.52   344.9 1005.66   354.8 1003.08
   364.8  1000.3   374.8 1001.44   394.8 1004.95   414.8 1006.73   574.9 1008.84
   584.6 1009.16   604.2 1011.82     614 1015.11   633.5 1026.91     653 1037.33
   682.3 1054.09   711.6 1068.75   721.4  1072.9   740.9 1077.51   760.4 1084.45
     780 1093.44   799.5 1104.33   828.8 1118.33   848.3 1126.54   887.4 1141.66
#Mann= 3 , 0 , 0
       0     .05       0   354.8    .045       0   374.8     .05       0
Bank Sta=354.8,374.8
XS Rating Curve= 0 ,0
Exp/Cntr=0.3,0.1

Type RM Length L Ch R = 1 ,28437.7 ,288.7,276.4,265
XS GIS Cut Line= 4
     1767178.053      425509.461     1767518.765      425263.801
     1767768.765      425105.815     1767950.623      424996.006
#Sta/Elev= 30
       0 1182.53    19.5 1180.44    58.6 1173.12    97.7 1161.38   117.2 1152.57
   136.8 1147.02   156.3  1137.2   166.1 1134.41     254 1096.49   283.3 1081.93
   312.6 1068.84   322.4    1065   332.1 1063.78   361.4  1049.4   390.7 1032.94
   429.9 1016.92   439.8 1010.82   459.5 1007.23   498.9 1005.13     627  1005.4
   653.8  999.04   656.6  998.51   668.8  999.03   676.3 1000.61   686.2 1004.83
   725.4 1028.64   783.4 1055.96   812.3  1066.4   870.3 1082.53   928.2 1106.49
#Mann= 3 , 0 , 0
       0     .05       0   653.8    .045       0   668.8      .1       0
#XS Ineff= 2 , 0
          531.59 1010.79
Permanent Ineff=
       F       F
Bank Sta=653.8,668.8
XS Rating Curve= 0 ,0
Exp/Cntr=0.3,0.1

Type RM Length L Ch R = 1 ,28161.3 ,567,576.5,585
XS GIS Cut Line= 4
     1767471.022       426071.31     1767689.772      425630.555
     1767883.348      425250.997     1767998.366      425038.324
#Sta/Elev= 30
       0  1015.5    19.7 1011.89    29.5 1011.16   177.1 1008.52   226.3 1009.07
   334.6 1008.86   442.8 1007.38     611 1003.84   769.5 1004.26   779.4 1004.02
   789.3 1000.57   799.2  998.39   809.1  997.92     819  998.92   838.8 1004.02
   848.8 1008.25   858.7  1013.6   878.5 1020.58   898.3 1022.89   908.2 1022.42
   918.1 1023.35   927.8 1027.14   947.1 1036.06   985.8 1050.84  1014.8 1058.67
  1034.2 1062.45  1053.5 1067.06  1063.2 1070.07  1111.6 1087.56  1159.9 1106.71
#Mann= 3 , 0 , 0
       0     .05       0   799.2    .045       0     819      .1       0
#XS Ineff= 2 , 0
          568.34 1010.95
Permanent Ineff=
       F       F
Bank Sta=799.2,819
XS Rating Curve= 0 ,0
Exp/Cntr=0.3,0.1

Type RM Length L Ch R = 1 ,27584.8 ,507.7,504,500.6
XS GIS Cut Line= 3
     1767859.477      426041.145     1768193.678      425761.197
     1768425.883      425581.076
#Sta/Elev= 30
       0 1066.98    29.7 1062.48    69.4 1054.28   128.8 1039.25   148.6 1031.19
   168.4 1017.67   178.4 1012.67   198.2 1012.57   227.9 1007.67   257.6  1004.9
     327  1002.5     426 1001.16   452.7   997.8   455.6  997.45   465.4  997.58
   467.7  998.56   475.1 1001.71   484.9 1009.95   494.7 1020.59   504.5 1029.58
   514.3 1037.34   524.1 1043.62   533.9 1048.37   543.7 1052.22   573.1 1060.56
   602.5 1064.82   612.3 1067.12   631.9 1075.02   690.6 1091.97   729.8 1107.42
#Mann= 3 , 0 , 0
       0     .05       0   452.7    .045       0   467.7      .1       0
Bank Sta=452.7,467.7
XS Rating Curve= 0 ,0
Exp/Cntr=0.3,0.1

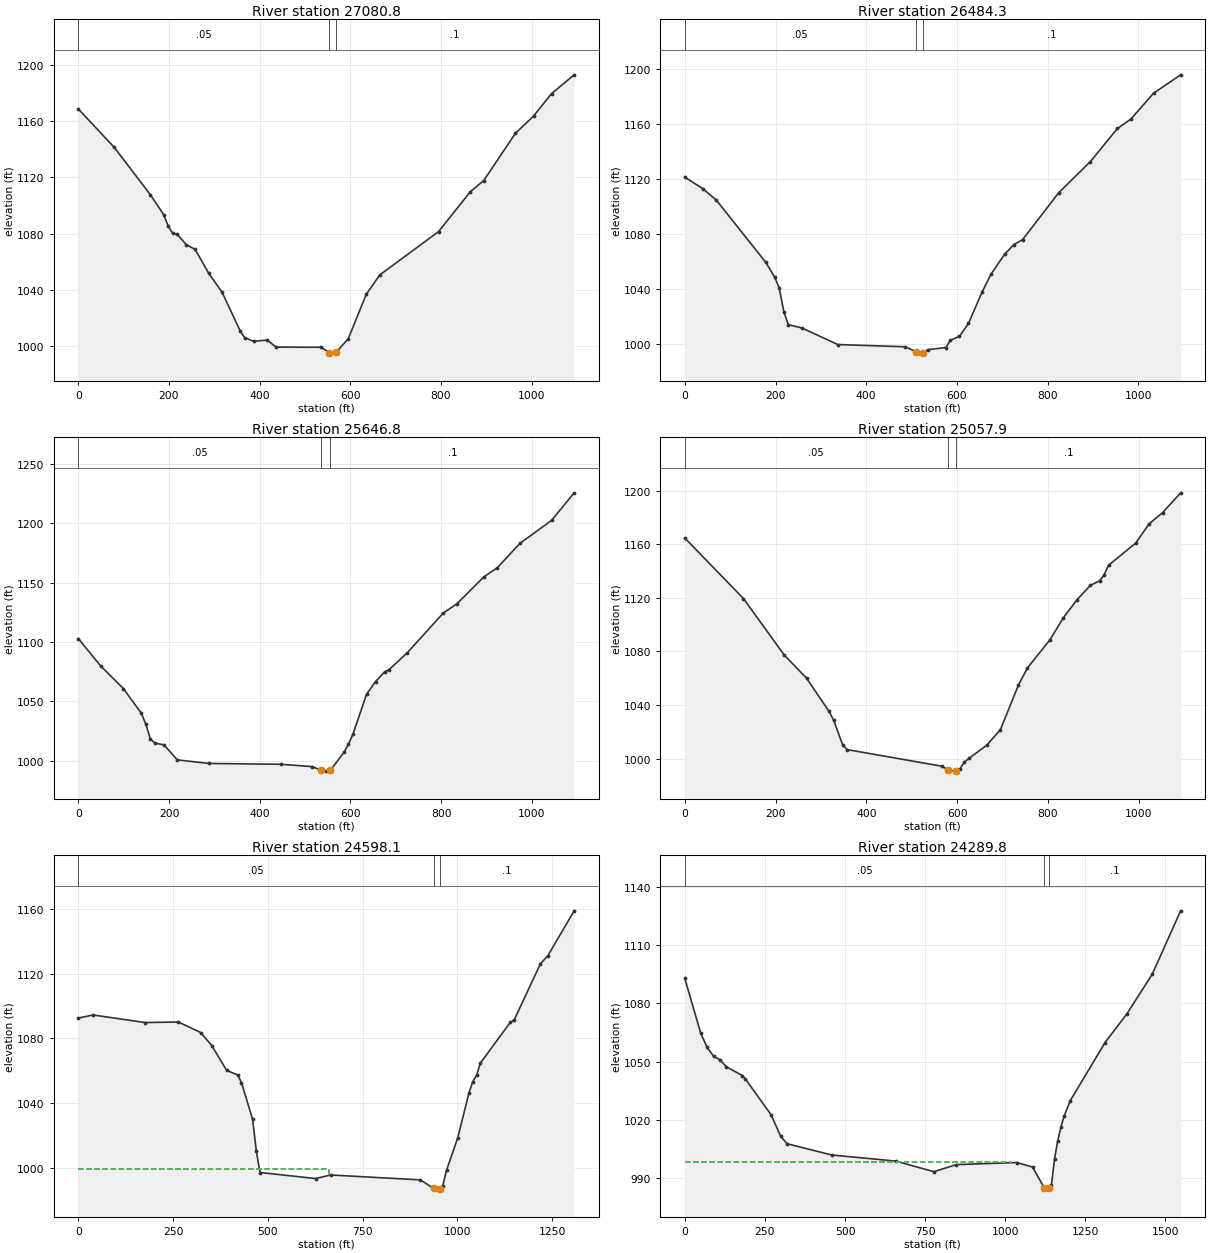
Type RM Length L Ch R = 1 ,27080.8 ,599,596.5,593.7
XS GIS Cut Line= 3
     1768122.654      426581.645     1768479.525      426169.014
     1768857.934      425771.859
#Sta/Elev= 30
       0 1168.57    79.4 1141.31   158.7 1107.81   188.5 1093.51   198.4 1085.29
   208.3  1080.3   218.2  1079.6   238.1 1072.26   257.9 1068.83   287.6 1051.94
   317.4 1038.41   357.1    1011     367 1006.24   386.8 1003.62   416.6 1004.52
   436.4   999.5   535.6  999.37   553.9  995.52   565.5  995.22   568.9  995.92
   595.4 1005.28   635.3 1036.95   665.2 1050.75   794.9 1081.52   864.7 1109.73
   894.6 1117.79   964.4 1151.29  1004.4 1163.54  1044.2 1179.49  1094.1 1192.85
#Mann= 3 , 0 , 0
       0     .05       0   553.9    .045       0   568.9      .1       0
Bank Sta=553.9,568.9
XS Rating Curve= 0 ,0
Exp/Cntr=0.3,0.1

Type RM Length L Ch R = 1 ,26484.3 ,833.8,837.4,839.2
XS GIS Cut Line= 3
     1768667.047      426918.683     1768990.792      426479.314
     1769312.186      426036.263
#Sta/Elev= 30
       0 1121.06    39.7 1112.69    69.5  1104.4   178.6 1059.12   198.5 1048.27
   208.4 1040.17   218.3 1023.35   228.2 1013.89     258 1011.49   337.4  999.43
   486.2  997.81   509.3   994.3     516   993.2   525.9  993.55   535.8  995.75
   575.6  997.25   585.6 1002.59   605.5 1005.41   625.4 1014.73   655.2 1037.44
   675.1 1050.57     705    1065   724.9 1071.91   744.8  1075.7   824.4 1109.74
   894.1 1132.34   953.8 1156.43   983.6 1163.29  1033.4 1182.04  1093.1 1195.41
#Mann= 3 , 0 , 0
       0     .05       0   509.3    .045       0   525.9      .1       0
Bank Sta=509.3,525.9
XS Rating Curve= 0 ,0
Exp/Cntr=0.3,0.1

Type RM Length L Ch R = 1 ,25646.8 ,592.8,588.9,586.5
XS GIS Cut Line= 3
     1769300.044      427259.828     1769682.586      426870.572
     1770040.696      426456.644
#Sta/Elev= 30
       0 1102.76    49.6 1079.68    99.2 1060.81   138.9    1040   148.8 1030.77
   158.8 1018.36   168.7 1014.93   188.5 1013.44   218.3 1000.75   287.8  997.76
   446.5  997.07     516  995.08   535.8  991.86   545.8   991.3   555.7  992.01
   585.6 1007.09   595.5 1013.95   605.5 1022.49   635.3 1055.85   655.2  1066.7
   675.1 1074.75   685.1 1076.72   724.9 1090.77   804.5  1124.3   834.4 1132.01
   894.1 1154.72   923.9  1162.5   973.7    1183  1043.3 1202.27  1093.1 1225.46
#Mann= 3 , 0 , 0
       0     .05       0   535.8    .045       0   555.7      .1       0
Bank Sta=535.8,555.7
XS Rating Curve= 0 ,0
Exp/Cntr=0.3,0.1

Type RM Length L Ch R = 1 ,25057.9 ,463.1,459.8,456.4
XS GIS Cut Line= 3
     1769768.661      427732.711     1770096.174      427295.306
     1770407.395      426846.782
#Sta/Elev= 30
       0 1164.57   129.2 1119.46   218.6 1077.51   268.2 1060.04   317.9 1035.19
   327.9 1028.66   347.7  1010.4   357.7 1006.74   566.3  994.35   579.4  991.67
   594.4  990.68  597.25990.8658     606  992.28   615.9  997.33   625.8 1000.13
   665.5 1010.09   695.3  1021.6     735 1054.79   754.9  1067.7   804.5 1088.65
   834.3 1105.21   864.1 1118.49   893.8 1129.35   913.7  1132.6   923.6  1136.9
   933.5 1144.26   993.1 1160.73  1022.9 1175.09  1052.6 1183.53  1092.4 1198.31
#Mann= 3 , 0 , 0
       0     .05       0   579.4    .045       0  597.25      .1       0
Bank Sta=579.4,597.25
XS Rating Curve= 0 ,0
Exp/Cntr=0.3,0.1

Type RM Length L Ch R = 1 ,24598.1 ,308.8,308.3,307.8
XS GIS Cut Line= 4
     1770068.678      428301.128     1770258.843      427981.724
     1770430.319      427629.151     1770677.038      427143.392
#Sta/Elev= 30
       0 1092.57    39.1 1094.45   176.1  1089.8   264.1  1090.1   322.8 1083.63
   352.2 1075.55   391.3 1060.24   420.7 1057.37   430.5 1052.74   459.9 1030.06
   469.7 1010.53   479.5  997.14   626.6  993.41   665.8  995.61   902.5  992.59
   938.4  987.28     952  986.87   953.4  987.19   961.9  989.11   971.8  998.56
  1001.5 1018.64  1031.2 1046.56  1041.2 1053.34  1051.1 1057.25    1061 1064.68
  1140.2 1089.98  1150.1  1091.3  1219.5 1126.04  1239.3 1131.11  1308.6  1158.8
#Mann= 3 , 0 , 0
       0     .05       0   938.4    .045       0   953.4      .1       0
#XS Ineff= 2 , 0
          660.51  999.35
Permanent Ineff=
       F       F
Bank Sta=938.4,953.4
XS Rating Curve= 0 ,0
Exp/Cntr=0.3,0.1

Type RM Length L Ch R = 1 ,24289.8 ,519.4,520.6,521.7
XS GIS Cut Line= 3
     1770431.091      428728.645       1770686.3       427775.52
     1770932.083      427271.839
#Sta/Elev= 30
       0 1092.85    49.8 1064.52    69.8 1057.29    89.7 1052.78   109.6 1050.92
   129.6 1047.33   179.4 1042.82   189.4 1040.98   269.1 1022.65     299 1011.62
   318.9 1007.72   458.5 1001.91   657.8  998.78   777.4  993.32   847.2  996.96
  1035.9  998.03    1085  995.73  1121.7  984.98  1124.4  984.34  1136.7   984.9
    1144  986.25  1153.8  999.96  1163.7 1009.22  1173.5 1016.18  1183.4 1021.82
    1203 1029.93  1311.2 1059.76    1380 1074.68  1458.7 1094.99  1547.2  1127.6
#Mann= 3 , 0 , 0
       0     .05       0  1121.7    .045       0  1136.7      .1       0
#XS Ineff= 2 , 0
          1016.5  998.28
Permanent Ineff=
       F       F
Bank Sta=1121.7,1136.7
XS Rating Curve= 0 ,0
Exp/Cntr=0.3,0.1

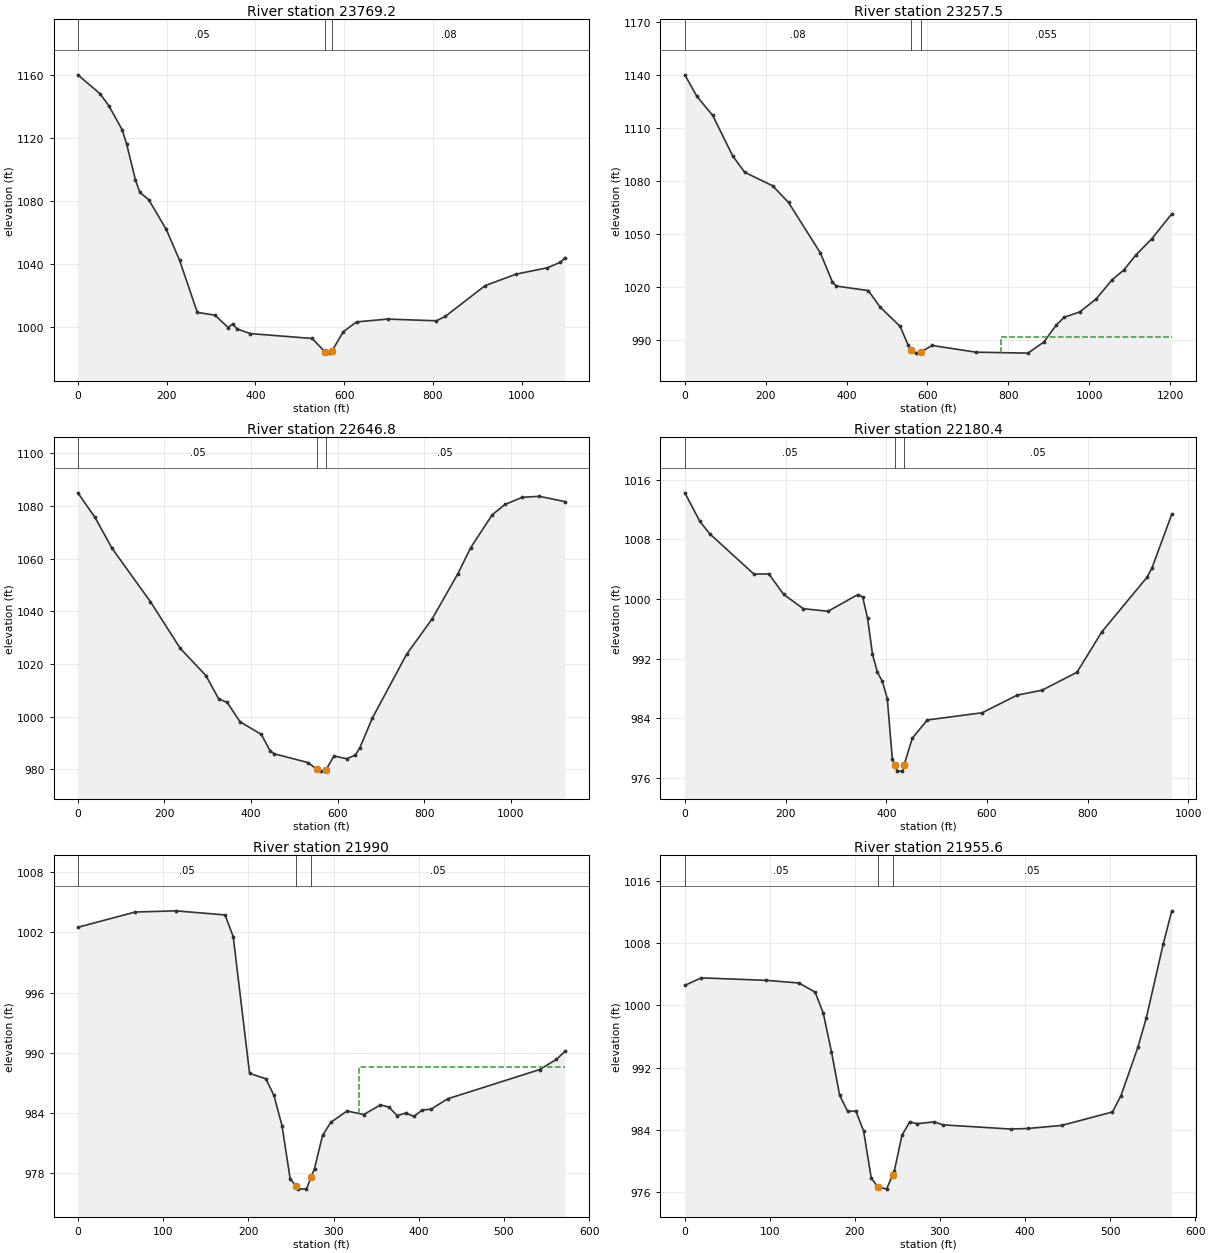
Type RM Length L Ch R = 1 ,23769.2 ,518.4,511.7,505.8
XS GIS Cut Line= 3
      1770978.21      428357.796     1771204.529      427891.839
     1771484.199      427384.752
#Sta/Elev= 30
       0 1159.87    49.8  1147.9    69.7 1140.31    99.6 1125.14   109.6 1116.28
   129.5 1093.49   139.5 1085.41   159.4 1080.87   199.2 1061.93   229.1 1042.48
     269 1009.44   308.8 1007.66   338.7  999.79   348.7 1002.14   358.6  998.92
   388.5  995.99     528   992.9   557.6  984.08   567.9  983.62   572.6  985.06
   597.9  997.16   627.8  1003.4   697.7 1005.18   807.6  1004.1   827.5 1006.83
   917.4 1026.34   987.3 1033.65  1057.2 1037.63  1087.1 1041.15  1097.1 1044.07
#Mann= 3 , 0 , 0
       0     .05       0   557.6    .045       0   572.6     .08       0
Bank Sta=557.6,572.6
XS Rating Curve= 0 ,0
Exp/Cntr=0.3,0.1

Type RM Length L Ch R = 1 ,23257.5 ,598.9,610.7,622.5
XS GIS Cut Line= 3
     1771610.207      428541.423     1771708.774      427948.007
     1771859.911      427364.496
#Sta/Elev= 30
       0 1140.16    29.6 1128.01      69 1117.13   118.3 1094.25   147.9 1084.95
     217 1077.31   256.4 1067.86   335.3 1039.21   364.9 1022.82   374.7 1020.48
   453.6 1017.93   483.2 1008.52   532.5  997.62   552.2  987.04   559.6  984.33
     572   982.6  582.88982.9784   611.4  986.84   720.1  983.03   848.6  982.49
   888.1  988.81   917.8  998.18   937.5  1002.7     977  1005.9  1016.6 1013.05
  1056.1 1023.88  1085.7 1029.62  1115.4 1038.08  1154.9 1047.28  1204.3 1061.43
#Mann= 3 , 0 , 0
       0     .08       0   559.6    .045       0  582.88    .055       0
#XS Ineff= 2 , 0
                          782.88          991.78
Permanent Ineff=
       F       F
Bank Sta=559.6,582.88
XS Rating Curve= 0 ,0
Exp/Cntr=0.3,0.1

Type RM Length L Ch R = 1 ,22646.8 ,473.4,466.4,457.8
XS GIS Cut Line= 3
     1771822.641      428589.732     1772188.878      428163.775
     1772578.692      427757.583
#Sta/Elev= 30
       0 1085.01    39.4  1075.7    78.8 1063.98   167.5 1043.69   236.5 1025.97
   295.7 1015.64   325.2  1006.8   344.9 1005.46   374.5  998.11   423.8  993.29
   443.5  987.17   453.4  985.95   532.2  982.59   551.9  980.03   561.8  979.37
  572.44979.6898   591.4  985.12     621  984.06   640.8  985.47   650.6  988.01
   680.3  999.56   759.3 1023.74   818.6 1037.24   877.8 1054.37   907.4 1064.23
   956.8 1076.64   986.5 1080.59    1026 1083.29  1065.5 1083.69  1124.7 1081.68
#Mann= 3 , 0 , 0
       0     .05       0   551.9    .045       0  572.44     .05       0
Bank Sta=551.9,572.44
XS Rating Curve= 0 ,0
Exp/Cntr=0.3,0.1

Type RM Length L Ch R = 1 ,22180.4 ,177.3,190.4,203.7
XS GIS Cut Line= 3
     1772289.327      428665.856       1772574.7      428382.652
     1772790.629      427860.734
#Sta/Elev= 30
       0 1014.24    29.4 1010.46      49 1008.77   137.3 1003.33   166.7 1003.37
   196.1 1000.62   235.3  998.69   284.4  998.35   343.2 1000.58     353 1000.28
   362.8  997.43   372.6  992.59   382.4  990.14   392.2  988.96     402  986.62
     412  978.49  416.57977.7632   421.9  976.91   431.8   976.9   435.3  977.73
   451.6  981.31   481.3  983.76   590.3  984.73   659.7  987.09   709.2  987.76
   778.6  990.16   828.1   995.6   917.3 1002.88   927.2  1004.1   966.9 1011.38
#Mann= 3 , 0 , 0
       0     .05       0  416.57    .045       0   435.3     .05       0
Bank Sta=416.57,435.3
XS Rating Curve= 0 ,0
Exp/Cntr=0.3,0.1

Type RM Length L Ch R = 1 ,21990   ,37.3,34.4,31.5
XS GIS Cut Line= 4
      1772566.02       428576.88     1772715.488      428427.864
     1772802.294       428369.27      1772902.12       428133.81
#Sta/Elev= 30
       0 1002.51    67.2 1004.03   115.1 1004.15   172.7 1003.74   182.3 1001.58
   201.5  987.96   220.6  987.42   230.1  985.76   239.6  982.74   249.1  977.47
   255.8976.7577   258.6  976.46   268.2  976.43   273.6   977.6   277.7  978.48
   287.2   981.8   296.8  983.08   315.8  984.21   335.5  983.86   355.1  984.82
     365   984.6   374.8  983.75   384.6     984   394.5  983.68   404.3  984.32
   414.2  984.38   433.8  985.42     542  988.34   561.7  989.36   571.5  990.14
#Mann= 3 , 0 , 0
       0     .05       0   255.8    .045       0   273.6     .05       0
#XS Ineff= 2 , 0
                           330.1          988.59
Permanent Ineff=
       F       F
Bank Sta=255.8,273.6
XS Rating Curve= 0 ,0
Exp/Cntr=0.3,0.1

Type RM Length L Ch R = 1 ,21955.6 ,112.8,111.1,109.4
XS GIS Cut Line= 4
     1772608.066      428586.284     1772754.551       428448.48
     1772808.804      428400.737     1772961.799      428143.576
#Sta/Elev= 30
       0 1002.57    19.2 1003.54    95.8 1003.22   134.1 1002.88   153.2 1001.71
   162.8     999   172.4  994.07     182  988.48   191.5   986.4   201.1  986.46
   210.2  983.88   219.2  977.86  226.62976.7552   237.2  976.43   244.5  978.29
   246.3  978.75   255.3  983.34   264.4  985.05   273.4  984.83   293.3  985.06
   303.3  984.68   383.1  984.14     403  984.21     443   984.6   502.8  986.33
   512.8  988.42   532.7  994.62   542.7  998.44   562.6 1007.92   572.6 1012.14
#Mann= 3 , 0 , 0
       0     .05       0  226.62    .045       0   244.5     .05       0
Bank Sta=226.62,244.5
XS Rating Curve= 0 ,0
Exp/Cntr=0.3,0.1

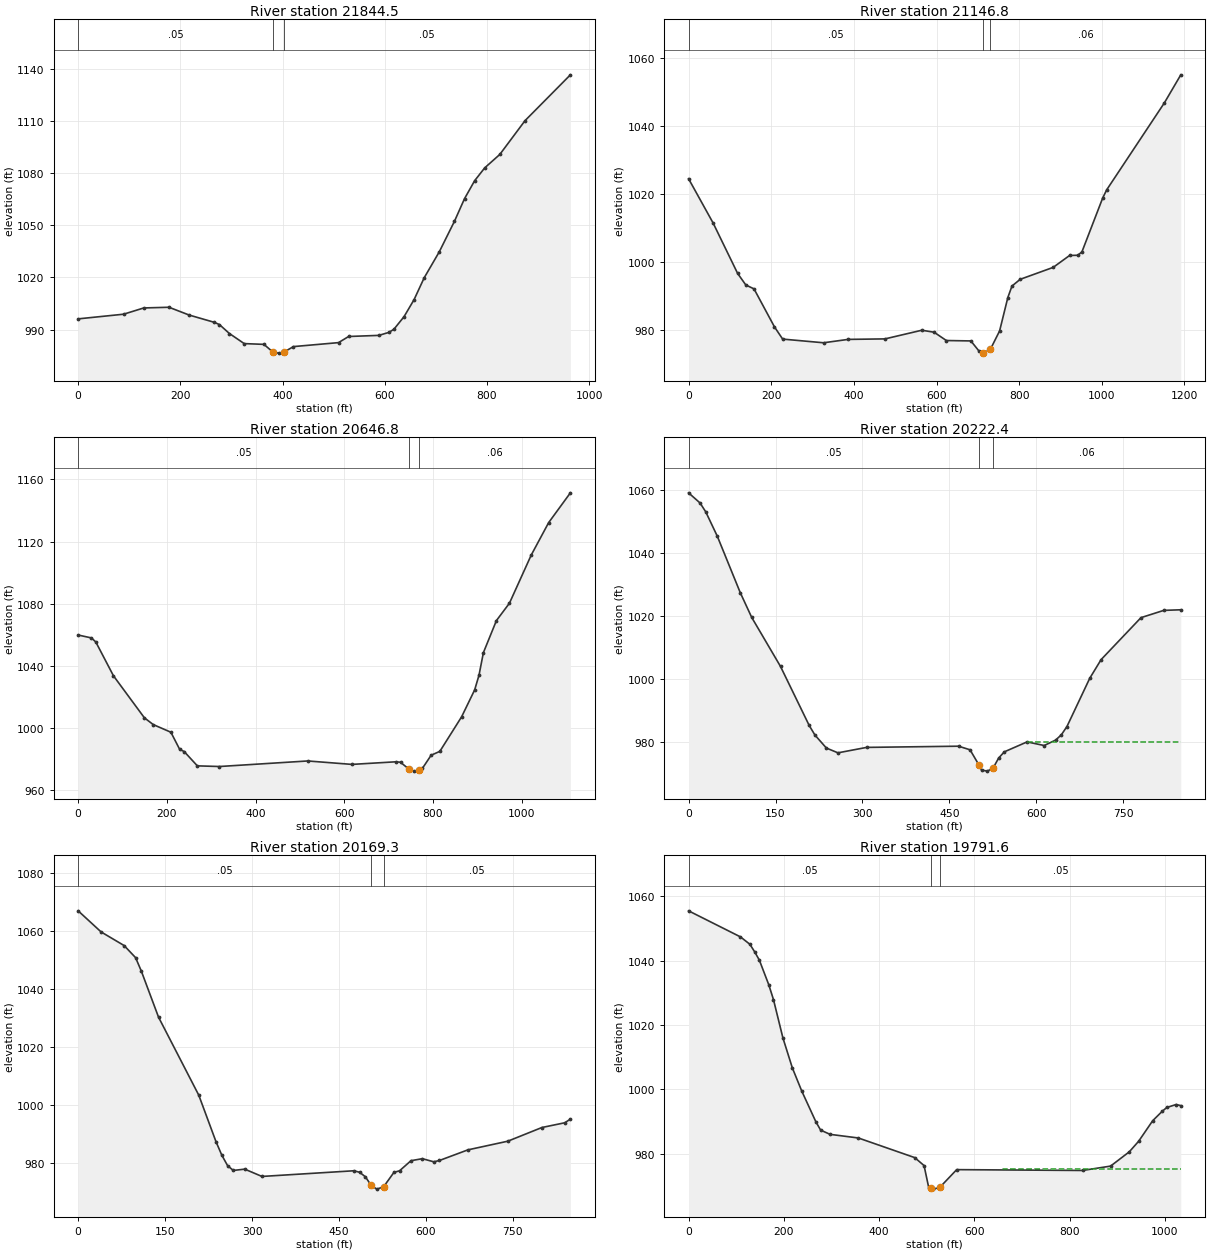
Type RM Length L Ch R = 1 ,21844.5 ,672.1,697.6,724
XS GIS Cut Line= 4
     1772513.231      428653.992     1772788.671      428575.586
     1772903.205      428458.246     1773254.551      428084.548
#Sta/Elev= 30
       0  996.14    88.9  998.82   128.4 1002.42   177.8 1002.82   217.3  998.33
   266.6  994.14   276.5  992.85     296  987.72     325  981.91   363.6  981.47
  381.67976.9072   392.5  976.43   402.5     977   421.4  980.19   509.5  982.47
   529.3     986   588.4  986.64   608.2  988.37     618  990.19   637.8  997.42
   657.5 1007.26   677.2 1019.78   706.8 1034.76   736.4 1052.27   756.1 1065.28
   775.9 1075.62   795.6    1083   825.2 1090.74   874.5 1110.17   963.3 1136.54
#Mann= 3 , 0 , 0
       0     .05       0  381.67    .045       0   402.5     .05       0
Bank Sta=381.67,402.5
XS Rating Curve= 0 ,0
Exp/Cntr=0.3,0.1

Type RM Length L Ch R = 1 ,21146.8 ,490.6,500,512.9
XS GIS Cut Line= 3
     1772301.426       428806.77     1772990.267      429025.713
     1773430.539      429185.637
#Sta/Elev= 30
       0 1024.49    59.4 1011.49   118.8  996.67   138.6  993.29   158.4  992.15
   207.9  980.99   227.7  977.41   326.7  976.33   386.2  977.32   475.3  977.47
   564.4  980.01   594.1  979.43   623.8  976.99   683.2  976.87     703  973.87
  712.27973.3269   712.9  973.29   730.3  974.38   752.7  979.81   772.6   989.6
   782.6  992.98   802.5  994.96   882.3  998.46   922.1 1001.96   942.1 1002.02
     952 1003.04  1001.9 1018.74  1011.8 1021.22  1151.4 1046.75  1191.2 1054.99
#Mann= 3 , 0 , 0
       0     .05       0  712.27    .045       0   730.3     .06       0
Bank Sta=712.27,730.3
XS Rating Curve= 0 ,0
Exp/Cntr=0.3,0.1

Type RM Length L Ch R = 1 ,20646.8 ,410,424.4,431.8
XS GIS Cut Line= 3
     1772212.884      428836.284     1772742.152      429377.153
     1772948.995      429663.541
#Sta/Elev= 30
       0 1059.93    29.9 1058.07    39.8 1055.46    79.7 1033.66   149.4 1006.66
   169.3 1002.32   209.1   997.4     229  986.34     239  984.99   268.8  975.76
   318.6  975.34   517.8  978.91   617.4   976.7   716.9  978.38   726.9  978.07
   746.8  973.47   756.8  972.37  768.31972.8032   776.4  974.19     796  982.61
   815.6  985.08   864.7 1007.31   894.1 1024.61   903.9 1034.04   913.8 1048.57
   943.2 1069.22   972.6 1080.42  1021.7 1111.37    1061 1132.25    1110 1151.41
#Mann= 3 , 0 , 0
       0     .05       0   746.8    .045       0  768.31     .06       0
Bank Sta=746.8,768.31
XS Rating Curve= 0 ,0
Exp/Cntr=0.3,0.1

Type RM Length L Ch R = 1 ,20222.4 ,53.9,53.1,53.1
XS GIS Cut Line= 3
     1772221.348      428885.112     1772332.459      429378.168
     1772450.514      429701.084
#Sta/Elev= 30
       0 1058.97    19.8 1055.76    29.7 1052.93    49.6 1045.23    89.2 1027.37
     109 1019.52   158.6 1004.03   208.1  985.35     218  982.32   237.8   978.2
   257.7  976.69   307.2  978.41   465.8  978.79   485.6  977.65   500.9  972.86
   505.4  971.25   515.2   970.9   525.1  971.76   534.9  975.03   544.7     977
     584  980.15   613.5  979.01   633.1  980.71     643  982.36   652.8  985.02
   692.1 1000.28   711.7 1006.19   780.5 1019.47   819.8 1021.77   849.2 1021.96
#Mann= 3 , 0 , 0
       0     .05       0   500.9    .045       0   525.1     .06       0
#XS Ineff= 2 , 0
                          583.28           980.1
Permanent Ineff=
       F       F
Bank Sta=500.9,525.1
XS Rating Curve= 0 ,0
Exp/Cntr=0.3,0.1

Type RM Length L Ch R = 1 ,20169.3 ,405.8,377.7,351.4
XS GIS Cut Line= 3
     1772169.264      428897.265     1772280.375       429390.32
     1772398.431      429713.237
#Sta/Elev= 30
       0 1066.96    39.6 1059.67    79.3 1054.97    99.1 1050.79     109 1046.14
   138.7 1030.23   208.1  1003.3   237.8  987.25   247.8   982.6   257.7     979
   267.6  977.31   287.4  977.76   317.1  975.24   475.7   977.2   485.6  976.68
   495.5  975.13   505.4   972.2   515.2  970.86  526.88971.6505   544.7  976.62
   554.5   977.2   574.2  980.68   593.8  981.37   613.5   980.3   623.3  980.75
   672.4  984.42   741.2  987.41   800.1  992.14   839.4  993.77   849.2  995.03
#Mann= 3 , 0 , 0
       0     .05       0   505.4    .045       0  526.88     .05       0
Bank Sta=505.4,526.88
XS Rating Curve= 0 ,0
Exp/Cntr=0.3,0.1

Type RM Length L Ch R = 1 ,19791.6 ,330.8,324.6,318.8
XS GIS Cut Line= 4
     1771450.514      429650.737     1771879.334      429574.348
      1772327.25      429619.487     1772405.375      429744.487
#Sta/Elev= 30
       0 1055.46   108.9 1047.36   128.7 1045.06   138.6 1042.74   148.5 1040.16
   168.3  1032.5   178.2 1027.87     198 1015.96   217.8 1006.64   237.6  999.42
   267.3  989.85   277.2  987.29     297  985.97   356.4  984.84   474.7  978.74
   494.3  976.26   504.1  969.42  508.91969.1852   513.9  968.94   527.5  969.51
   562.8     975     827  974.74   885.8   976.1   925.1  980.54   944.7  983.82
   974.2  990.21   993.8  993.08  1003.7  994.32  1023.3  995.24  1033.2   994.9
#Mann= 3 , 0 , 0
       0     .05       0  508.91    .045       0   527.5     .05       0
#XS Ineff= 2 , 0
                          660.86          975.06
Permanent Ineff=
       F       F
Bank Sta=508.91,527.5
XS Rating Curve= 0 ,0
Exp/Cntr=0.3,0.1