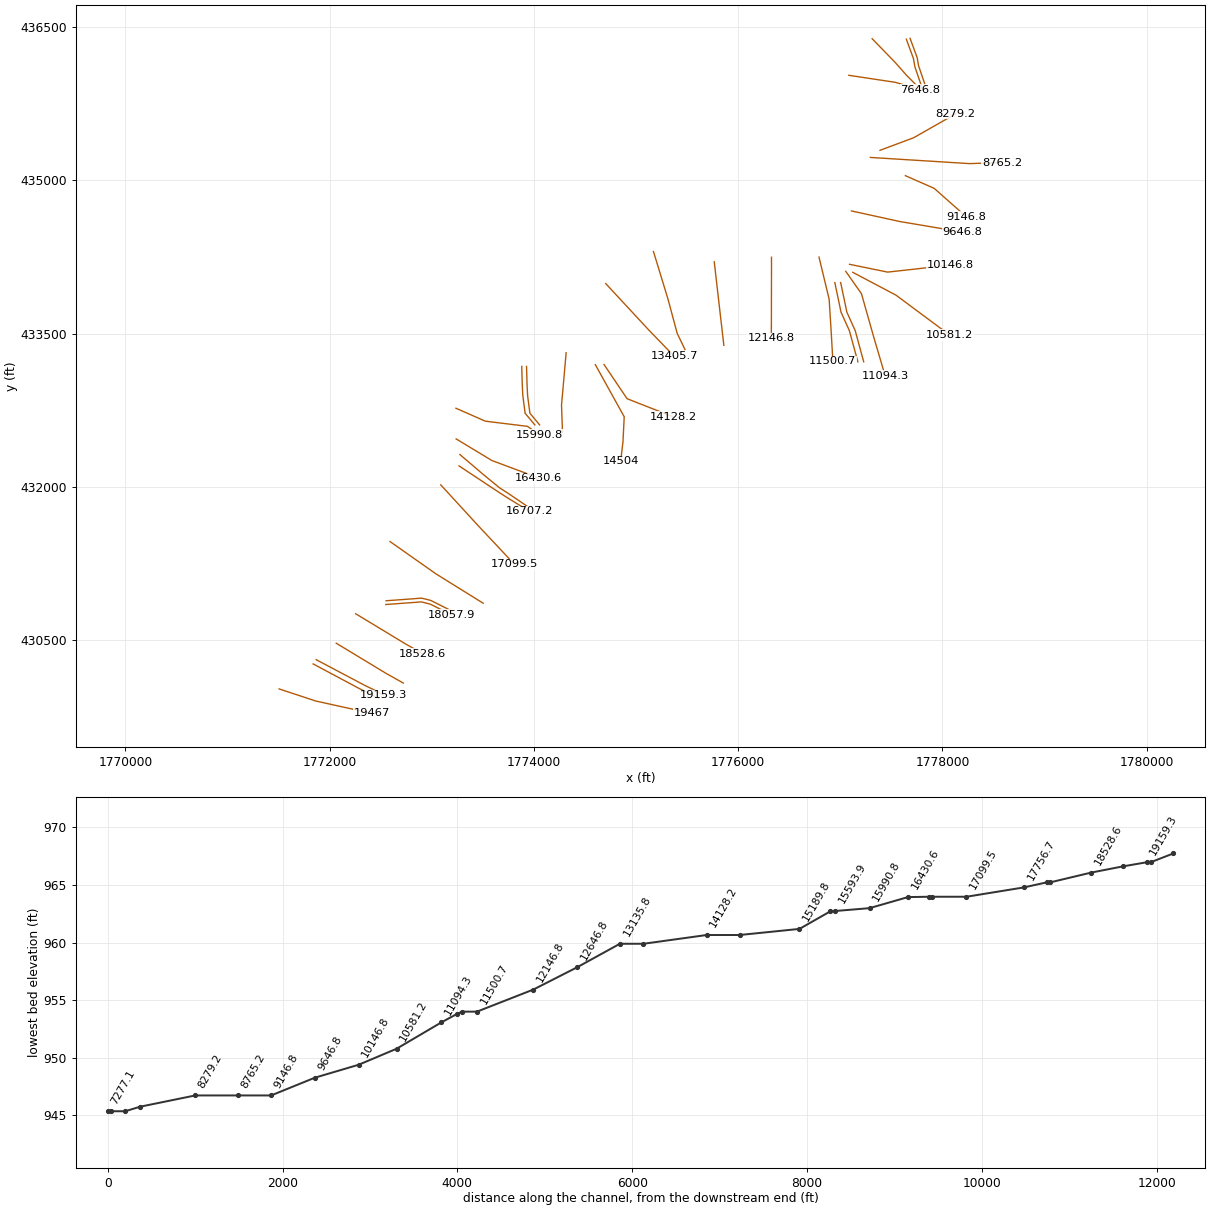
HEC-RAS study DaysRun.prj: DaysRun

--- DaysRun.g01 (geometry) --- (continued)

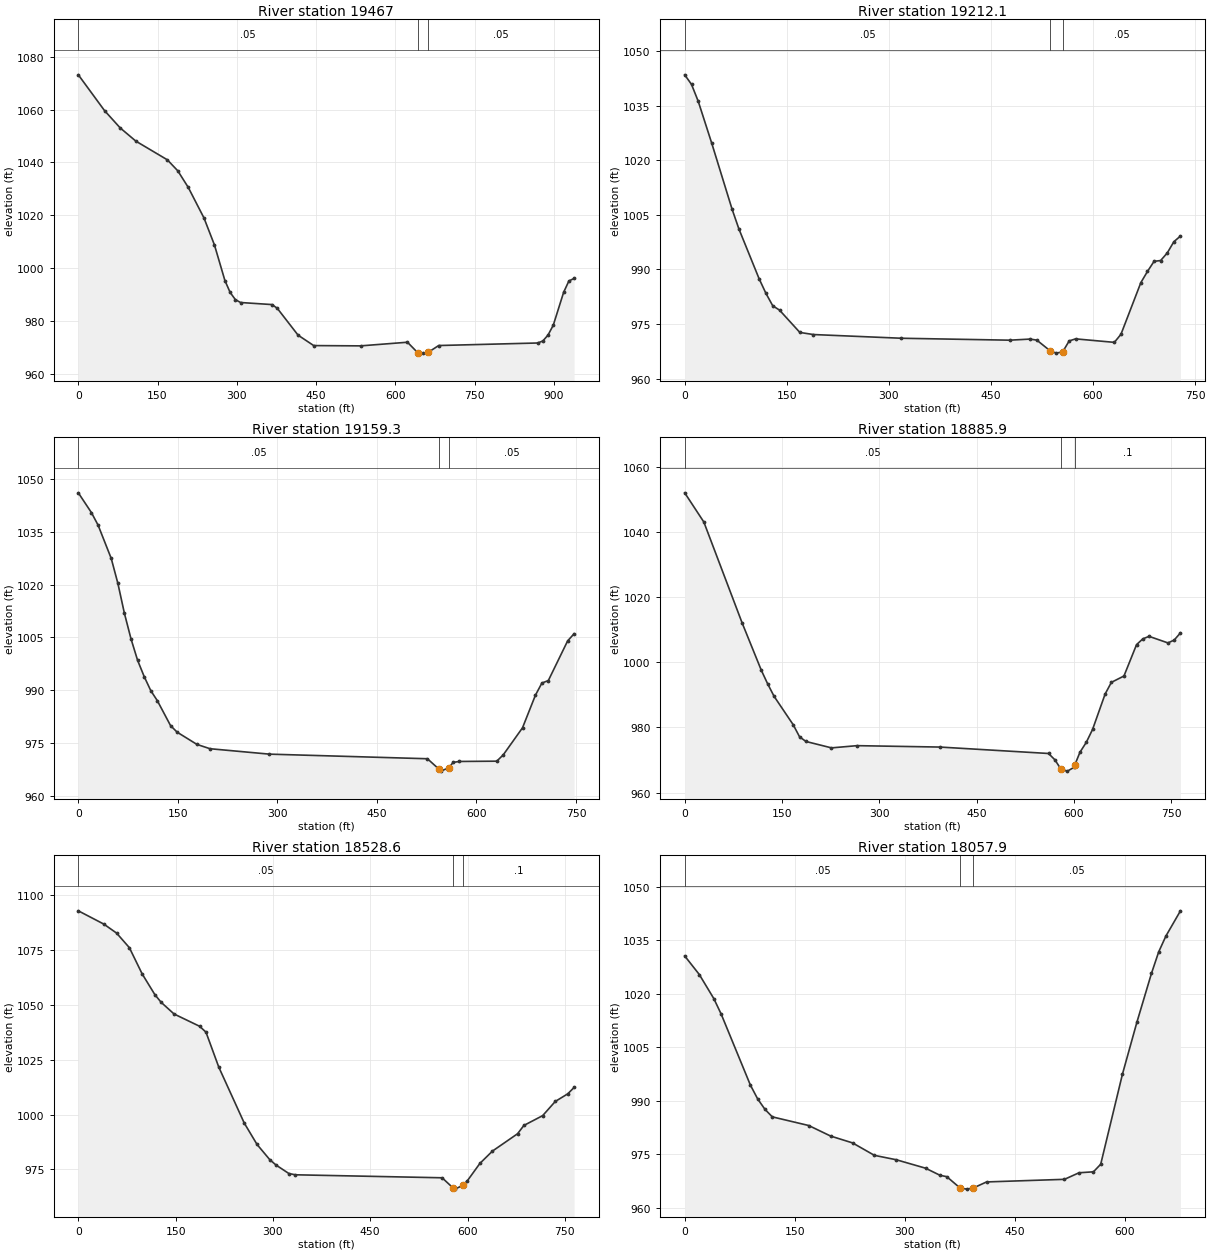
Type RM Length L Ch R = 1 ,19467   ,261.4,254.9,248
XS GIS Cut Line= 3
     1771504.334      430020.529     1771861.973      429902.473
     1772410.584      429780.945
#Sta/Elev= 30
       0  1073.2    49.6 1059.64    79.3 1053.07     109 1048.06   168.5 1040.99
   188.3 1036.82   208.1 1030.54   237.9 1018.94   257.7 1008.72   277.5  995.24
   287.4  990.73   297.3  988.01   307.2  986.91   366.7  986.13   376.6  984.73
     416  974.54   445.6  970.59   534.4  970.48   623.1  971.86  642.21967.9537
   652.6  967.73   662.5  968.05   682.2  970.61   869.5  971.57   879.4  972.34
   889.2  974.58   899.1   978.3   918.8  990.81   928.7  995.08   938.5  996.04
#Mann= 3 , 0 , 0
       0     .05       0  642.21    .045       0   662.5     .05       0
Bank Sta=642.21,662.5
XS Rating Curve= 0 ,0
Exp/Cntr=0.3,0.1

Type RM Length L Ch R = 1 ,19212.1 ,53.4,52.8,55.2
XS GIS Cut Line= 4
     1771837.667       430265.32     1772302.945      430017.056
     1772379.334      429980.598     1772481.764      429925.043
#Sta/Elev= 30
       0 1043.49      10 1040.86    19.9  1036.2    39.8 1024.64    69.6 1006.56
    79.6 1001.14   109.4   987.4   119.4   983.4   129.4  979.99   139.3  978.81
   169.2  972.67   189.1  972.09   318.4  971.07   477.6  970.54   507.5  970.84
   517.4  970.56   536.8  967.65   546.2  966.98   555.5  967.35     565  970.34
   574.4   970.9   631.4  969.94   641.1  972.17   670.3  986.36     680  989.43
   689.7  992.21   699.4  992.44   709.1  994.52   718.8   997.6   728.5  999.17
#Mann= 3 , 0 , 0
       0     .05       0   536.8    .045       0   555.5     .05       0
Bank Sta=536.8,555.5
XS Rating Curve= 0 ,0
Exp/Cntr=0.3,0.1

Type RM Length L Ch R = 1 ,19159.3 ,273.8,273.4,269.8
XS GIS Cut Line= 4
     1771867.181      430306.987      1772349.82      430051.779
     1772426.209       430015.32     1772528.639      429959.765
#Sta/Elev= 30
       0 1046.09    19.8 1040.45    29.8 1036.89    49.6 1027.43    59.6 1020.34
    69.5 1011.79    79.4 1004.56    89.3  998.48    99.3  993.82   109.2  989.84
   119.1  986.98     139   979.9   148.9  978.04   178.7  974.56   198.5  973.33
   287.9  971.79   526.1  970.48   543.1  967.59     546  966.96   558.1  967.87
   564.8  969.44   574.2  969.71   630.6  969.79   640.3  971.57   669.4  979.28
   688.9  988.57   698.6     992   708.3  992.71   737.4 1003.99   747.1 1006.02
#Mann= 3 , 0 , 0
       0     .05       0   543.1    .045       0   558.1     .05       0
Bank Sta=543.1,558.1
XS Rating Curve= 0 ,0
Exp/Cntr=0.3,0.1

Type RM Length L Ch R = 1 ,18885.9 ,358,357.2,356.8
XS GIS Cut Line= 3
     1772064.188      430467.919     1772552.444      430172.381
     1772721.348       430077.82
#Sta/Elev= 30
       0 1051.94    29.5 1042.99    88.6 1012.01   118.1  997.53   127.9  993.36
   137.8  989.54   167.3  980.82   177.1  977.11     187  975.69   226.3  973.73
   265.7  974.41   393.6  973.98   560.9  972.01   570.7  970.08   580.4   967.1
   590.1   966.6   599.8  967.72   601.4   968.5   609.4   972.4   619.1  975.42
   628.8  979.38   648.2  990.26   657.8  993.82   677.2  995.77   696.6 1005.38
   706.2 1007.15   715.9 1007.93     745 1005.92   754.6 1006.78   764.3    1009
#Mann= 3 , 0 , 0
       0     .05       0   580.4    .045       0   601.4      .1       0
Bank Sta=580.4,601.4
XS Rating Curve= 0 ,0
Exp/Cntr=0.3,0.1

Type RM Length L Ch R = 1 ,18528.6 ,460.7,470.7,479.1
XS GIS Cut Line= 3
      1772255.16      430756.114     1772743.417      430460.575
      1772912.32      430366.015
#Sta/Elev= 30
       0 1092.64    39.4 1086.59      59 1082.51    78.7 1075.88    98.4 1063.96
   118.1 1054.47   127.9 1050.97   147.6 1045.72     187 1040.13   196.8 1037.46
   216.5 1021.58   255.8  996.12   275.5   986.4   295.2  979.45     305  976.98
   324.7  973.15   334.6  972.59   560.9  971.23   577.6  966.64   580.4  966.07
   592.6  967.73   599.8  969.88   619.1  977.76   638.5  983.38   677.2  991.26
   686.9  995.03   715.9   999.5   735.3 1005.94   754.6 1009.42   764.3  1012.3
#Mann= 3 , 0 , 0
       0     .05       0   577.6    .045       0   592.6      .1       0
Bank Sta=577.6,592.6
XS Rating Curve= 0 ,0
Exp/Cntr=0.3,0.1

Type RM Length L Ch R = 1 ,18057.9 ,42.4,39.4,37.7
XS GIS Cut Line= 4
     1772549.473      430846.918     1772896.984      430872.525
     1772984.875      430850.824     1773197.042      430744.487
#Sta/Elev= 30
       0 1030.66    19.9 1025.45    39.8 1018.66    49.8 1014.32    89.6  994.42
    99.6  990.51   109.5  987.61   119.5   985.5   169.2  983.07   199.1  980.11
     229  978.19   258.8   974.7   288.7  973.46   328.5   971.1   348.4  969.09
   357.5  968.72   375.6  965.55   384.7  965.22   393.7  965.54   411.8  967.24
   518.1  967.97   537.9  969.81   557.6  970.08   567.5   972.2   597.2  997.51
     617 1012.14   636.8 1025.79   646.6 1031.79   656.5 1036.26   676.3 1043.32
#Mann= 3 , 0 , 0
       0     .05       0   375.6    .045       0   393.7     .05       0
Bank Sta=375.6,393.7
XS Rating Curve= 0 ,0
Exp/Cntr=0.3,0.1

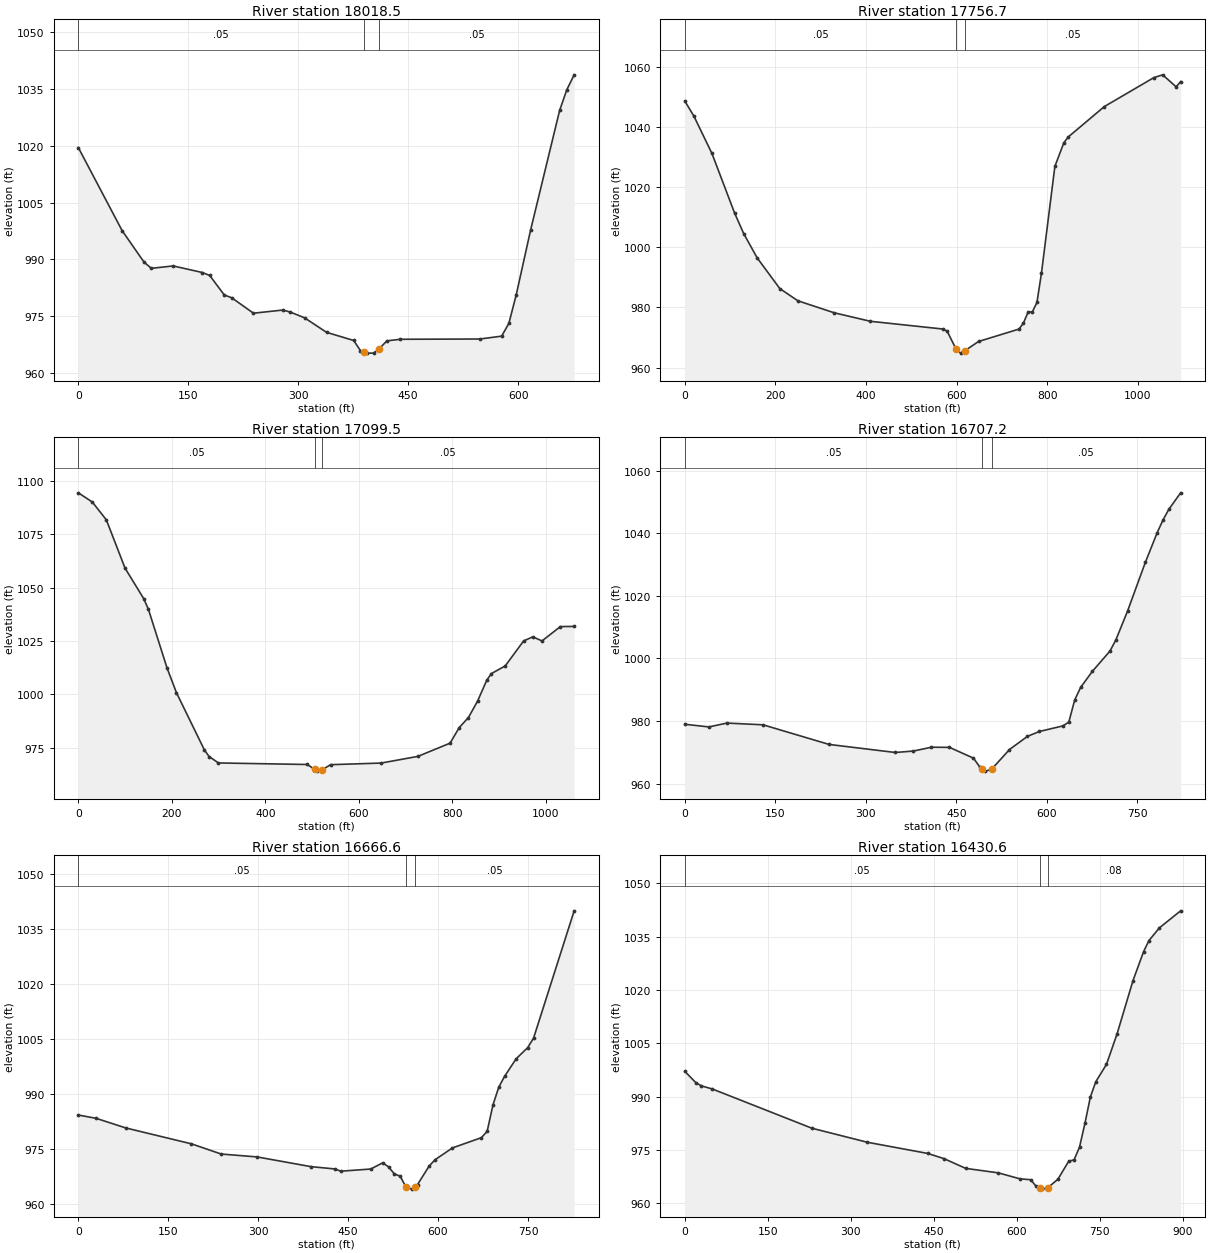
Type RM Length L Ch R = 1 ,18018.5 ,269.1,261.8,254.8
XS GIS Cut Line= 4
     1772552.728       430883.81     1772900.239      430909.418
      1772988.13      430887.716     1773200.297      430781.379
#Sta/Elev= 30
       0 1019.53    59.7   997.6    89.6  989.27    99.6  987.63   129.4  988.26
   169.2  986.52   179.2  985.74   199.1  980.58   209.1  979.86   238.9  975.77
   278.8   976.6   288.7   976.1   308.6  974.55   338.5  970.72   375.6  968.56
   384.7  965.91  389.59965.5351   393.7  965.22   402.8  965.22   410.2  966.35
   420.9  968.46     439  968.88   547.8  968.95   577.4  969.71   587.3  973.11
   597.2  980.56     617  997.83   656.5 1029.36   666.4 1034.87   676.3 1038.76
#Mann= 3 , 0 , 0
       0     .05       0  389.59    .045       0   410.2     .05       0
Bank Sta=389.59,410.2
XS Rating Curve= 0 ,0
Exp/Cntr=0.3,0.1

Type RM Length L Ch R = 1 ,17756.7 ,663.2,657.1,650.7
XS GIS Cut Line= 3
     1772590.729      431463.719     1773040.041      431147.542
     1773503.004      430859.653
#Sta/Elev= 30
       0 1048.56      20 1043.58    59.9 1031.15   109.9 1011.36   129.9 1004.54
   159.8  996.43   209.8  986.23   249.7  982.17   329.6   978.2   409.6  975.36
   569.2   972.8   579.1  972.09     599  966.07   608.9  964.78   618.8  965.63
   648.5  968.65   737.7  972.77   747.6  974.76   757.6  978.34   767.5  978.56
   777.4  981.61   787.3  991.28     817 1026.85   836.9 1034.74   846.8 1036.66
   926.1 1046.72  1035.1 1056.32  1054.9 1057.28  1084.7 1053.29  1094.6 1055.03
#Mann= 3 , 0 , 0
       0     .05       0     599    .045       0   618.8     .05       0
Bank Sta=599,618.8
XS Rating Curve= 0 ,0
Exp/Cntr=0.3,0.1

Type RM Length L Ch R = 1 ,17099.5 ,386.9,392.4,397.8
XS GIS Cut Line= 3
     1773087.305       432019.01     1773451.889       431621.44
     1773808.354      431241.478
#Sta/Elev= 30
       0 1094.44      30 1090.11    59.9 1081.78    99.9 1059.13   139.8 1044.85
   149.8 1039.88   189.8 1012.28   209.8 1000.76   269.7  973.86   279.7  970.81
   299.7   967.8   489.5  967.08   505.5  964.81   509.5  963.97   520.5  964.44
   539.4  966.99   647.6  967.75   726.2  970.88     795  977.08   814.7  984.42
   834.3  989.09     854  996.87   873.6 1006.64   883.5 1009.71     913 1013.29
   952.3 1025.01     972 1026.92   991.6 1025.01  1030.9 1031.72  1060.4 1031.82
#Mann= 3 , 0 , 0
       0     .05       0   505.5    .045       0   520.5     .05       0
Bank Sta=505.5,520.5
XS Rating Curve= 0 ,0
Exp/Cntr=0.3,0.1

Type RM Length L Ch R = 1 ,16707.2 ,40.5,40.5,40.6
XS GIS Cut Line= 4
     1773266.125      432204.773      1773656.75      431946.093
     1773748.764      431887.065     1773957.097      431760.329
#Sta/Elev= 30
       0  978.95    39.9   978.1    69.8  979.33   129.6  978.78   239.2   972.5
   348.9  969.93   378.8  970.39   408.7  971.61   438.6  971.57   478.4  968.12
   488.4  965.42   492.7  964.79   498.3  963.97   508.3  964.53   538.1  970.88
   567.9  975.09   587.6  976.64   626.6  978.43   636.4  979.65   646.1  986.67
   655.9  990.71   675.4  995.86   704.6 1002.35   714.4 1005.92   733.9 1015.21
   763.2 1030.69   782.7 1040.13   792.4 1044.23   802.2 1047.67   821.7 1052.94
#Mann= 3 , 0 , 0
       0     .05       0   492.7    .045       0   508.3     .05       0
Bank Sta=492.7,508.3
XS Rating Curve= 0 ,0
Exp/Cntr=0.3,0.1

Type RM Length L Ch R = 1 ,16666.6 ,231.3,236.1,240.8
XS GIS Cut Line= 5
     1773274.805      432315.885      1773509.18      432116.232
     1773663.694      431989.496     1773745.291      431937.412
     1773929.319      431812.412
#Sta/Elev= 30
       0  984.21    29.8   983.3    79.4  980.67   188.7  976.34   238.4  973.55
     298  972.77   387.8  970.12   427.8  969.48   437.8  968.87   487.7  969.46
   507.7  971.16   517.4  970.04   527.1  968.12   536.8  967.51   546.1  964.65
   556.1  963.97   561.1  964.62   565.8  965.23   585.2  970.29   594.8  971.97
   623.9  975.22   672.2  978.02   681.9  979.76   691.6  986.97   701.2  991.79
   710.9  994.76   730.3  999.58   749.6 1002.64   759.3 1005.21     827 1039.98
#Mann= 3 , 0 , 0
       0     .05       0   546.1    .045       0   561.1     .05       0
Bank Sta=546.1,561.1
XS Rating Curve= 0 ,0
Exp/Cntr=0.3,0.1

Type RM Length L Ch R = 1 ,16430.6 ,434.1,439.8,444.4
XS GIS Cut Line= 4
     1773238.347      432468.662     1773589.041      432256.857
     1773910.222      432137.065     1774043.902      432084.982
#Sta/Elev= 30
       0  997.08      20  993.89      30     993      50   992.1   229.8  981.07
   329.8  977.13   439.1  973.98   468.5  972.51   507.6  969.78   566.4  968.52
   605.6  966.84   625.2  966.58     635  964.69   641.1  964.22   644.8  963.94
   656.1  964.36   674.1   966.7   693.7  971.76   703.5   972.2   713.3  975.76
   723.1  982.46   732.9  989.86   742.7  994.15     762  999.04   781.2 1007.65
   809.9 1022.59     829 1030.73   838.6 1033.84   857.7 1037.46     896 1042.24
#Mann= 3 , 0 , 0
       0     .05       0   641.1    .045       0   656.1     .08       0
Bank Sta=641.1,656.1
XS Rating Curve= 0 ,0
Exp/Cntr=0.3,0.1

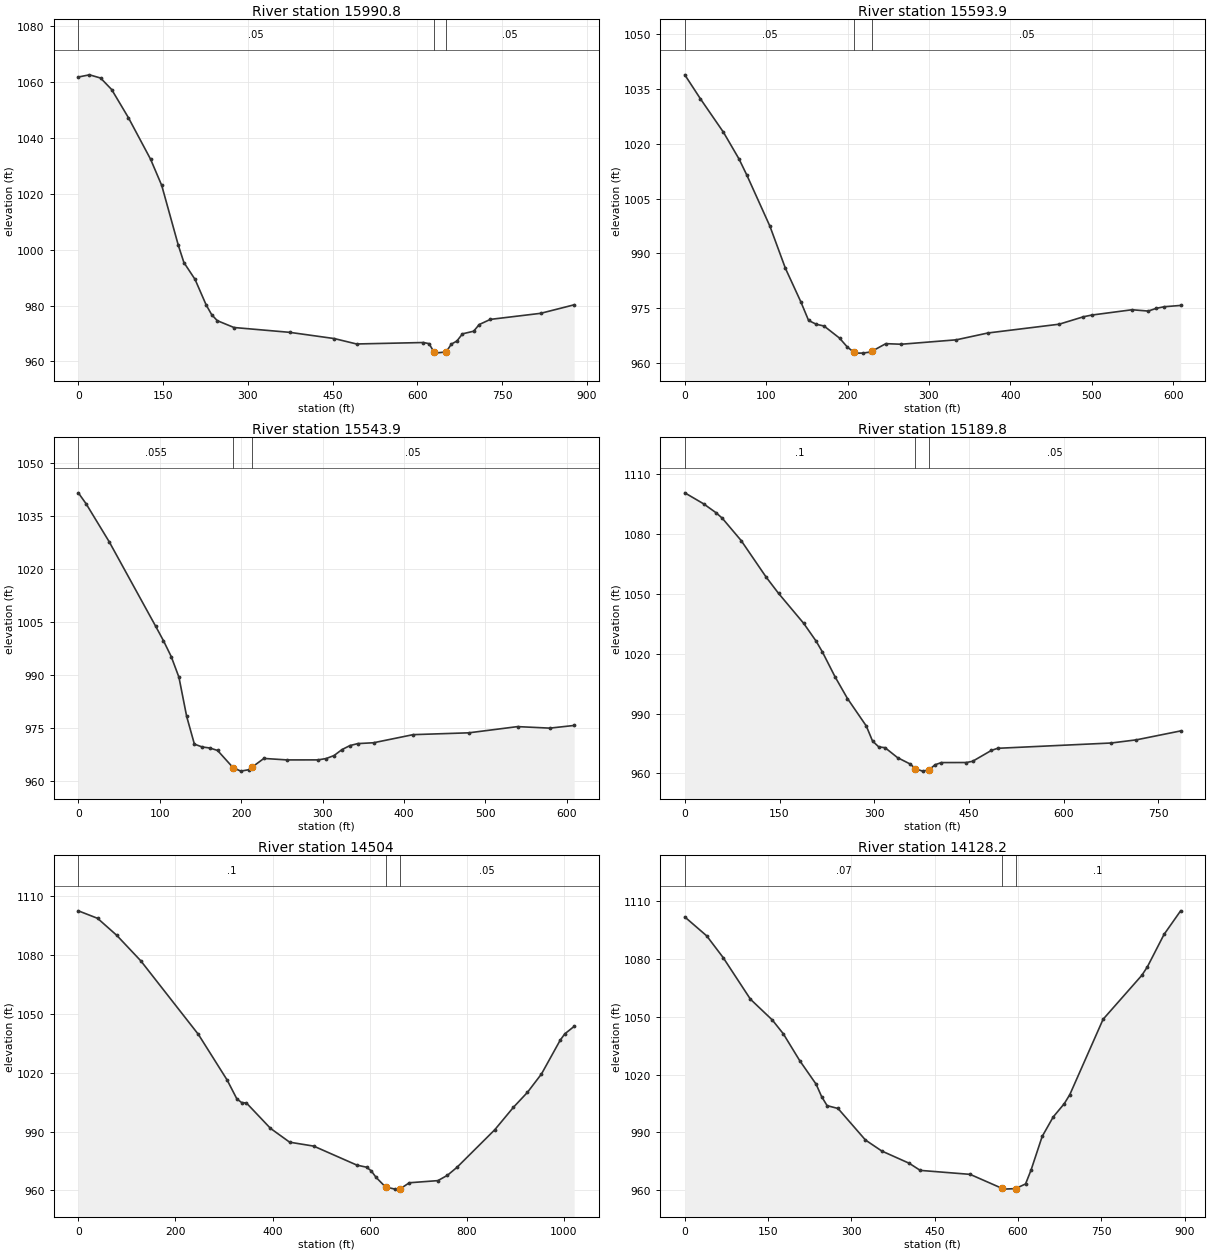
Type RM Length L Ch R = 1 ,15990.8 ,429.6,396.9,364.9
XS GIS Cut Line= 4
     1773236.611       432769.01     1773524.805      432642.273
     1773936.264      432591.926     1774057.791      432506.857
#Sta/Elev= 30
       0  1061.9    19.7 1062.68    39.4 1061.53      59 1057.41    88.6 1047.35
   127.9 1032.44   147.6 1023.07   177.1 1001.54   186.9  995.43   206.6   989.4
   226.3  980.24   236.1  976.74     246  974.61   275.5  972.16     374  970.43
     453   968.2   492.5  966.26   610.9  966.78   620.8  966.38     630963.2204
   630.7  962.98  651.09963.4098   660.3  966.21   670.1  967.31     680  969.89
   699.8  970.83   709.6  973.22   729.4  975.07   818.4  977.24   877.7  980.29
#Mann= 3 , 0 , 0
       0     .05       0     630    .045       0  651.09     .05       0
Bank Sta=630,651.09
XS Rating Curve= 0 ,0
Exp/Cntr=0.3,0.1

Type RM Length L Ch R = 1 ,15593.9 ,49.4,50,50.5
XS GIS Cut Line= 5
     1773880.708      433178.732     1773885.916      432998.176
     1773891.125       432894.01     1773913.694      432720.398
      1774009.18      432605.815
#Sta/Elev= 30
       0 1038.82      19 1032.33    47.5 1023.12    66.6 1015.82    76.1 1011.46
   104.6  997.42   123.6  985.93   142.6  976.74   152.1  971.66   161.6  970.62
   171.1  970.14   190.1  966.84   199.6  964.42  207.91962.9417   209.1  962.73
   218.6  962.74     228  963.03  230.21963.2823     247  965.32     266  965.16
   333.6  966.37   372.5  968.24     460  970.64   489.8  972.67   499.8  973.13
   549.5  974.59   569.4  974.23   579.3  974.98   589.3  975.42   609.2  975.77
#Mann= 3 , 0 , 0
       0     .05       0  207.91    .045       0  230.21     .05       0
Bank Sta=207.91,230.21
XS Rating Curve= 0 ,0
Exp/Cntr=0.3,0.1

Type RM Length L Ch R = 1 ,15543.9 ,357.3,354.2,351.2
XS GIS Cut Line= 5
     1773927.583      433178.732     1773932.791      432998.176
        1773938.       432894.01     1773960.569      432720.398
     1774056.055      432605.815
#Sta/Elev= 30
       0 1041.67     9.5 1038.58      38 1027.76    95.1 1003.78   104.6  999.71
   114.1  995.23   123.6  989.36   133.1  978.24   142.6  970.37   152.1  969.57
   161.6  969.27   171.1  968.57   190.1   963.7   199.6  962.71   209.1   963.1
  213.08963.7716     228  966.31   256.5  965.89   294.6   965.9   304.4  966.28
   314.1  967.12   323.8   968.8   333.6  969.95   343.3  970.52   362.7  970.76
   411.4  973.06   479.9  973.58   539.6  975.34   579.3  974.91   609.2  975.67
#Mann= 3 , 0 , 0
       0    .055       0   190.1    .045       0  213.08     .05       0
Bank Sta=190.1,213.08
XS Rating Curve= 0 ,0
Exp/Cntr=0.3,0.1

Type RM Length L Ch R = 1 ,15189.8 ,683.2,685.8,687.8
XS GIS Cut Line= 3
     1774315.522      433312.471     1774270.196      432799.215
     1774280.014      432529.426
#Sta/Elev= 30
       0  1100.8    29.7  1095.3    49.5 1090.81    59.4 1088.05    89.2 1076.88
   128.8 1058.53   148.6 1050.31   188.3 1035.31   208.1 1026.33     218 1020.92
   237.8 1008.59   257.6   997.6   287.4  983.83   297.3  976.28   307.2  973.32
   317.1  972.95   336.9  967.95   356.7  964.78   365.3   962.4   376.5  961.18
   386.4  961.78   396.4  964.38   406.3  965.47   445.9   965.5   455.8  966.12
   485.5  971.57   495.4  972.63   675.2  975.29   715.2  976.88   785.2  981.35
#Mann= 3 , 0 , 0
       0      .1       0   365.3    .045       0   386.4     .05       0
Bank Sta=365.3,386.4
XS Rating Curve= 0 ,0
Exp/Cntr=0.3,0.1

Type RM Length L Ch R = 1 ,14504   ,347.1,375.8,404.4
XS GIS Cut Line= 4
     1774601.194      433196.093      1774884.18      432685.676
     1774872.027      432440.885     1774849.458      432249.912
#Sta/Elev= 30
       0 1102.66    39.6 1098.84    79.1 1090.16   128.6 1077.15   247.3 1039.57
   306.6 1016.24   326.4 1006.72   336.3 1004.81   346.2  1004.6   395.7  991.65
   435.2   984.6   484.7   982.6   573.7  972.89   593.4  971.85   603.2  969.96
     613  966.68   632.6  961.74   652.2  960.65  662.67960.7874   681.6   963.9
   740.5  964.99   760.1  967.72   779.7  971.77   857.6  990.97     896 1002.42
   924.9 1010.06   953.7 1019.41   992.2 1036.63  1001.8 1039.91    1021 1043.69
#Mann= 3 , 0 , 0
       0      .1       0   632.6    .045       0  662.67     .05       0
Bank Sta=632.6,662.67
XS Rating Curve= 0 ,0
Exp/Cntr=0.3,0.1

Type RM Length L Ch R = 1 ,14128.2 ,732.4,722.5,712.7
XS GIS Cut Line= 3
     1774686.264      433197.829     1774911.958       432862.76
     1775366.819       432683.94
#Sta/Elev= 30
       0 1101.64    39.4 1091.85      69 1080.62   118.2 1059.02   157.7 1048.23
   177.4  1041.1   206.9 1027.21   236.5 1014.98   246.3  1008.6   256.2  1003.9
   275.9 1002.42   325.2   986.1   354.7  980.38     404  974.05   423.9  970.36
   513.7   968.3  571.54960.9982   573.6  960.65  595.54960.9195   613.5  963.34
   623.4  970.52   643.4  987.92   663.3  998.04   683.3 1004.95   693.2 1009.61
   753.1 1048.63   822.9 1071.42   832.9 1075.82   862.8 1092.57   892.7 1104.81
#Mann= 3 , 0 , 0
       0     .07       0  571.54    .045       0  595.54      .1       0
Bank Sta=571.54,595.54
XS Rating Curve= 0 ,0
Exp/Cntr=0.3,0.1

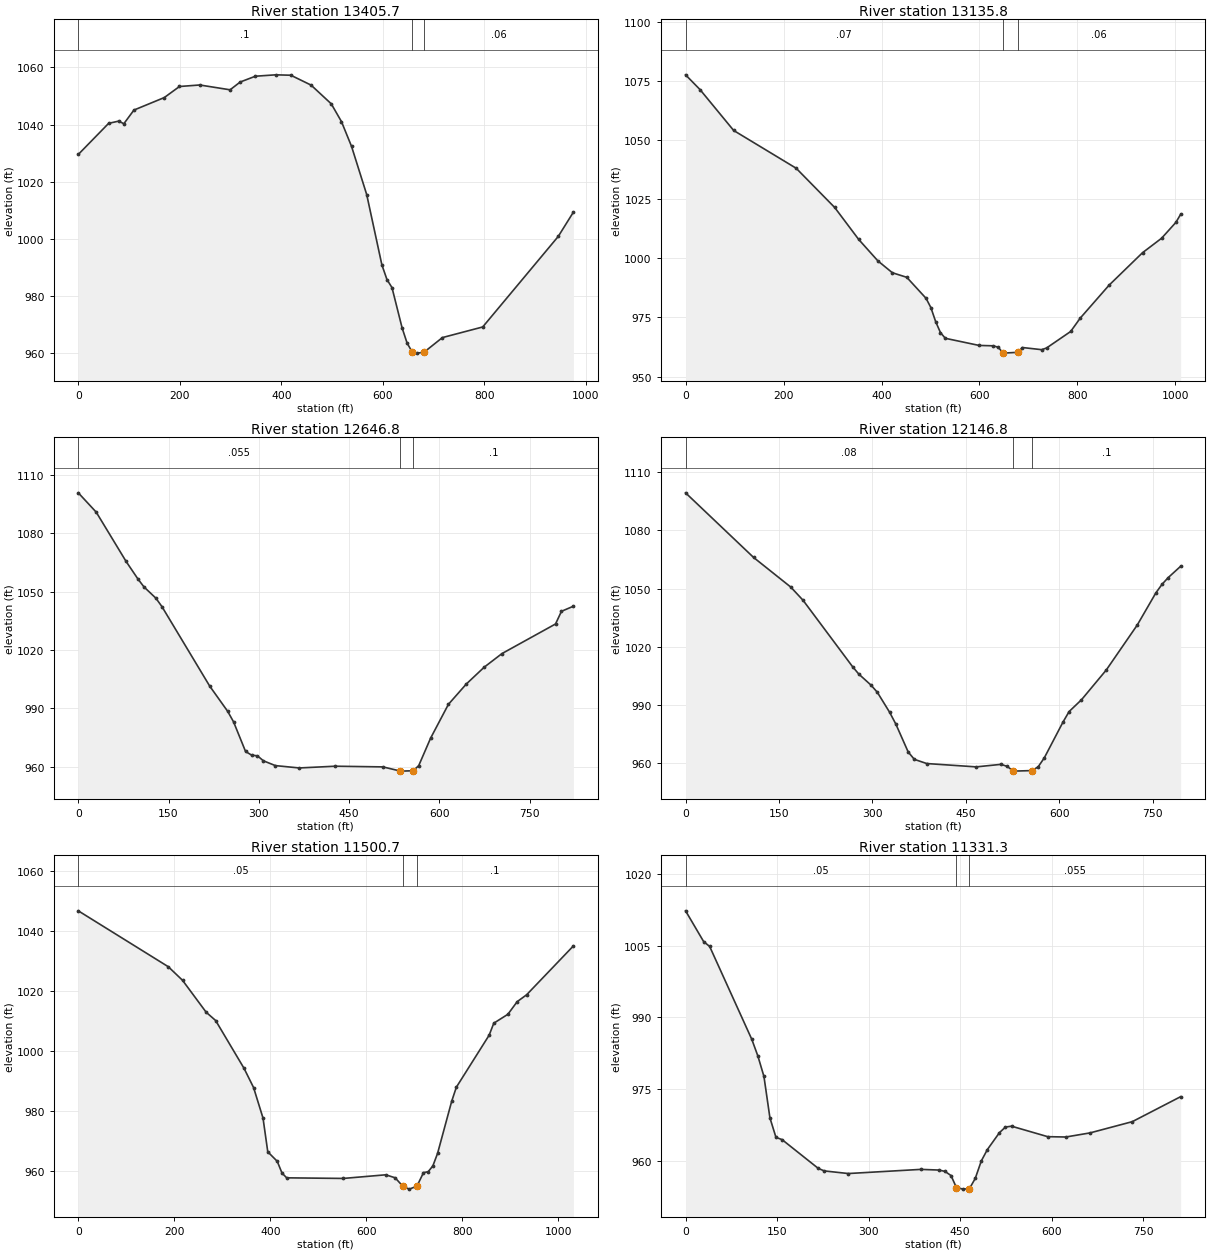
Type RM Length L Ch R = 1 ,13405.7 ,281.1,269.9,258.8
XS GIS Cut Line= 3
     1774703.625      433989.496     1775123.764      433536.371
     1775372.027      433279.426
#Sta/Elev= 30
       0 1029.52    59.8 1040.42    79.7  1041.2    89.7 1040.28   109.6 1045.07
   169.4 1049.45   199.3 1053.33   239.2 1053.86     299 1052.17   318.9  1054.9
   348.8 1056.93   388.7 1057.42   418.6 1057.28   458.5 1053.82   498.3 1047.25
   518.3 1041.05   538.2 1032.36   568.1 1015.45     598  990.81     608  985.67
   617.9  982.85   637.8  968.75   647.7  963.38   657.6  960.33   667.6  959.89
   680.8  960.18   717.2  965.34   796.6  969.06   945.4 1000.79   975.2  1009.3
#Mann= 3 , 0 , 0
       0      .1       0   657.6    .045       0   680.8     .06       0
Bank Sta=657.6,680.8
XS Rating Curve= 0 ,0
Exp/Cntr=0.3,0.1

Type RM Length L Ch R = 1 ,13135.8 ,492.7,489,485
XS GIS Cut Line= 4
     1775170.639      434303.732     1775311.264      433843.662
     1775403.277      433501.648     1775479.666      433343.662
#Sta/Elev= 30
       0 1077.62    29.4  1071.4    98.2 1054.08   225.8  1038.1   304.4 1021.51
   353.4 1007.99   392.7  998.89   422.2  993.89   451.6  991.96   490.9  983.08
   500.8  979.15   510.6  973.19   520.4  968.56   530.3  966.16   599.1  963.15
   628.6  962.98   638.5  962.34   647.7  960.04   648.3  959.89  678.41960.2331
   687.7  962.26     727  961.35   736.9  962.06   786.1  969.04   805.7   974.7
   864.5  988.62   932.8 1002.36   971.7 1008.48    1001 1015.21  1010.7 1018.63
#Mann= 3 , 0 , 0
       0     .07       0   647.7    .045       0  678.41     .06       0
Bank Sta=647.7,678.41
XS Rating Curve= 0 ,0
Exp/Cntr=0.3,0.1

Type RM Length L Ch R = 1 ,12646.8 ,502.6,500,497.3
XS GIS Cut Line= 3
     1775765.986      434202.877     1775828.072      433660.419
     1775859.875      433385.329
#Sta/Elev= 30
       0 1100.66    29.8 1090.74    79.4 1065.48    99.3 1056.37   109.2 1052.37
     129 1046.59     139 1042.28   218.4 1001.49   248.2  988.58   258.1  983.11
     278  967.94   287.9  966.09   297.8  965.68   307.8  963.13   327.6  960.68
   367.3  959.48   426.9  960.37   506.3  960.02  534.17957.9689   536.1  957.85
  556.54958.0403   565.8  960.65   585.6  974.78   615.2  992.13   644.9 1002.54
   674.6 1011.17   704.2 1018.17   793.2 1033.36   803.1 1039.86   822.9 1042.47
#Mann= 3 , 0 , 0
       0    .055       0  534.17    .045       0  556.54      .1       0
Bank Sta=534.17,556.54
XS Rating Curve= 0 ,0
Exp/Cntr=0.3,0.1

Type RM Length L Ch R = 1 ,12146.8 ,644.3,646.1,647.7
XS GIS Cut Line= 3
     1776326.771      434247.827     1776325.721      433701.778
     1776325.152      433453.037
#Sta/Elev= 30
       0 1099.41   109.2 1066.09   168.8 1050.84   188.6 1044.01   268.1 1009.77
     278 1005.99   297.8 1000.23   307.8  996.59   327.6  986.26   337.6  980.15
   357.4  965.78   367.3  961.98   387.2  959.83   466.6  958.11   506.3  959.41
   516.3  958.38   525.3956.1436   526.2  955.92     556   956.2     566  958.12
   575.9  962.77   605.8  981.15   615.7  986.63   635.6  992.72   675.4 1008.07
   725.1 1031.24     755 1047.82   764.9 1052.25   774.9 1055.73   794.8 1061.55
#Mann= 3 , 0 , 0
       0     .08       0   525.3    .045       0     556      .1       0
Bank Sta=525.3,556
XS Rating Curve= 0 ,0
Exp/Cntr=0.3,0.1

Type RM Length L Ch R = 1 ,11500.7 ,161.4,169.4,177.5
XS GIS Cut Line= 4
     1776791.807      434249.195     1776891.125      433836.718
     1776911.958      433503.385     1776927.583      433230.815
#Sta/Elev= 30
       0 1046.68   187.5 1028.06   217.1 1023.55   266.4  1012.9   286.1 1010.15
   345.3  994.21   365.1  987.83   384.8  977.65   394.7  966.42   414.4  963.27
   424.3  959.36   434.1  957.76     552  957.56   640.4  958.77     660  957.78
  676.46954.8856   689.5     954   705.5     955     719  959.48   728.8   959.8
   738.6  961.74   748.4  965.91   777.8  983.26   787.5  987.94   855.8 1005.26
   865.5 1009.26   894.8 1012.22   914.3 1016.44   933.8 1018.71  1031.3 1034.99
#Mann= 3 , 0 , 0
       0     .05       0  676.46    .045       0   705.5      .1       0
Bank Sta=676.46,705.5
XS Rating Curve= 0 ,0
Exp/Cntr=0.3,0.1

Type RM Length L Ch R = 1 ,11331.3 ,54,54,54
XS GIS Cut Line= 4
      1776946.68      433999.912     1777007.444      433709.982
     1777089.041      433529.426     1777172.375      433223.871
#Sta/Elev= 30
       0 1012.36    29.6 1005.91    39.5 1004.88   108.6  985.38   118.5   981.9
   128.4  977.63   138.2  968.94   148.1  964.85     158  964.39   217.2  958.37
   227.1  957.82   266.6  957.27   385.4  958.14   415.1     958     425  957.72
   434.9  956.84  443.72954.3276   454.7     954     465  954.09   474.6  956.25
   484.5  959.91   494.4  962.29   514.2  965.84   524.1  967.02     534   967.2
   593.3     965     623  964.93   662.6  965.79   731.9  968.15   811.1  973.39
#Mann= 3 , 0 , 0
       0     .05       0  443.72    .045       0     465    .055       0
Bank Sta=443.72,465
XS Rating Curve= 0 ,0
Exp/Cntr=0.3,0.1

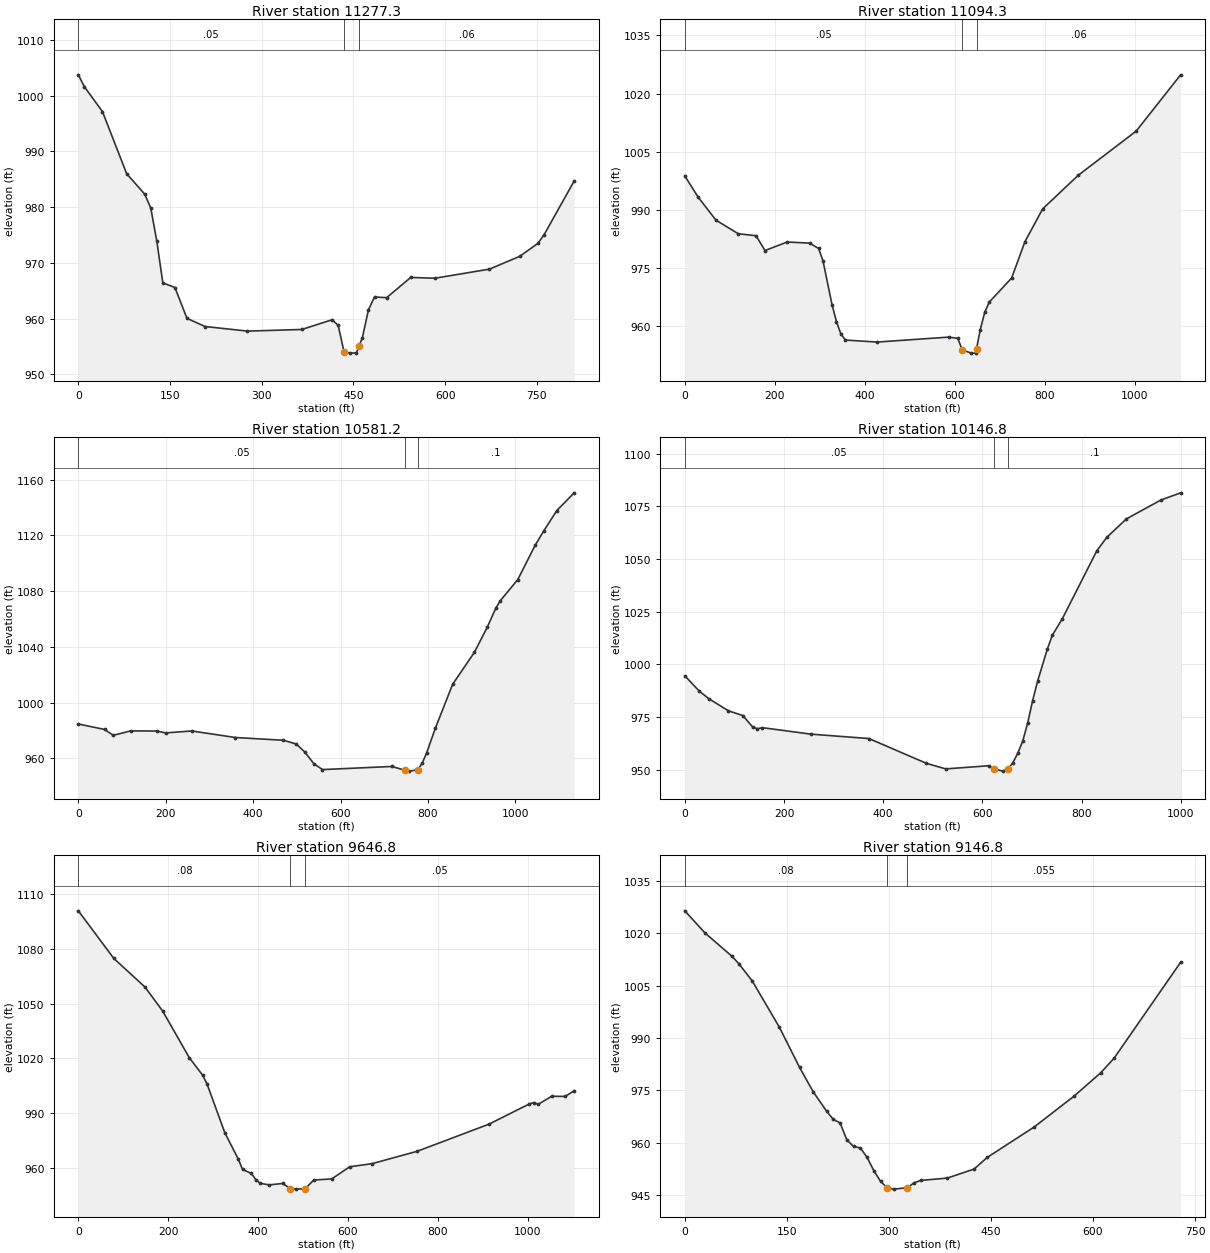
Type RM Length L Ch R = 1 ,11277.3 ,186.4,183.1,179.7
XS GIS Cut Line= 4
     1777003.972      433999.912     1777064.736      433709.982
     1777146.333      433529.426     1777229.666      433223.871
#Sta/Elev= 30
       0 1003.72     9.9 1001.58    39.5  997.12      79     986   108.6  982.32
   118.5  979.84   128.4  973.89   138.2  966.42     158  965.58   177.7  960.06
   207.4  958.59   276.5  957.77   365.6  958.06   415.1   959.8     425  958.82
  434.64954.0584   444.8  953.82   454.7  953.86  459.14955.0772   464.6  956.57
   474.6  961.59   484.5  963.89   504.3  963.76   543.8  967.39   583.4  967.25
   672.5  968.88     722  971.17   751.7  973.49   761.6  974.99   811.1  984.68
#Mann= 3 , 0 , 0
       0     .05       0  434.64    .045       0  459.14     .06       0
Bank Sta=434.64,459.14
XS Rating Curve= 0 ,0
Exp/Cntr=0.3,0.1

Type RM Length L Ch R = 1 ,11094.3 ,498.4,513.1,527.7
XS GIS Cut Line= 4
     1777053.845      434109.606     1777207.491      433890.856
     1777329.887      433458.564     1777439.262      433088.772
#Sta/Elev= 30
       0  998.75    29.7  993.29    69.3  987.35   118.8  983.85   158.4  983.34
   178.2  979.52   227.7  981.72   277.3  981.43   297.3  980.07   307.2  976.88
   327.2   965.6   337.2  961.17   347.2  957.94   357.2  956.44   427.1  955.92
   586.8   957.2   606.8  956.88   616.8  953.91   636.7  953.07   646.7  953.07
  648.64954.2321   656.7  959.06   666.7  963.58   676.7  966.21   726.5  972.42
   756.2  981.83   795.7  990.28   874.8  998.94  1003.4 1010.31  1102.2 1024.82
#Mann= 3 , 0 , 0
       0     .05       0   616.8    .045       0  648.64     .06       0
Bank Sta=616.8,648.64
XS Rating Curve= 0 ,0
Exp/Cntr=0.3,0.1

Type RM Length L Ch R = 1 ,10581.2 ,417.5,434.4,451.4
XS GIS Cut Line= 3
     1777122.027      434100.607     1777545.639      433876.648
      1778071.68      433486.023
#Sta/Elev= 30
       0  984.61    59.9   980.7    79.9   976.5   119.8  979.66   179.7  979.55
   199.6  978.21   259.6  979.59   359.4   974.9   469.2  972.93     499  970.19
   518.9  964.23   538.7  956.15   558.6  951.89   717.4  954.12   747.2  951.43
   757.1  950.78     777  951.76   786.9  956.66   796.8  963.74   816.7  981.48
   856.4 1013.12     906 1035.97   935.8 1054.22   955.7 1068.06   965.6 1073.16
  1005.3  1088.2    1045 1112.77  1064.9 1123.21  1094.7 1137.77  1134.4  1150.5
#Mann= 3 , 0 , 0
       0     .05       0   747.2    .045       0     777      .1       0
Bank Sta=747.2,777
XS Rating Curve= 0 ,0
Exp/Cntr=0.3,0.1

Type RM Length L Ch R = 1 ,10146.8 ,507.4,500,493.6
XS GIS Cut Line= 4
     1777090.777      434178.732     1777464.041      434102.343
      1777723.03      434131.009     1778078.625      434171.787
#Sta/Elev= 30
       0  994.64    29.3  987.34    48.8  983.71    87.9  978.02   117.2  975.74
   136.8  970.32   146.5   969.5   156.3  970.02     254  966.95   371.2  964.85
   487.2  953.08   525.8  950.45   612.6  951.94   622.3  950.46   641.6  949.39
   651.5  950.25   661.4  953.42   671.4  957.96   681.3  963.71   691.3  972.38
   701.2  982.85   711.2  992.09     731 1007.45     741 1013.92   760.9 1021.64
   830.5 1053.94   850.4 1060.27   890.1 1069.08   959.7 1078.05   999.5 1081.47
#Mann= 3 , 0 , 0
       0     .05       0   622.3    .045       0   651.5      .1       0
Bank Sta=622.3,651.5
XS Rating Curve= 0 ,0
Exp/Cntr=0.3,0.1

Type RM Length L Ch R = 1 ,9646.8  ,504.3,500,487.1
XS GIS Cut Line= 3
     1777109.875      434701.301     1777582.609      434597.858
     1778193.208      434494.704
#Sta/Elev= 30
       0 1100.84      79 1074.73   148.1 1059.11   187.6 1045.92   246.9 1020.33
   276.5 1010.75   286.4 1005.91   325.9  979.21   355.5  964.93   365.4  959.06
   385.2  956.86     395  953.44   404.9  951.47   424.7  950.59   454.3  951.37
  471.73 948.601   483.9  948.27  504.72948.5129   523.9  953.26   563.8  953.86
   603.8  960.52   653.7  962.24   753.6  968.99   913.4  983.86  1003.3  994.96
  1013.3  995.73  1023.3  994.77  1053.2  999.18  1083.2  999.08  1103.2 1002.16
#Mann= 3 , 0 , 0
       0     .08       0  471.73    .045       0  504.72     .05       0
Bank Sta=471.73,504.72
XS Rating Curve= 0 ,0
Exp/Cntr=0.3,0.1

Type RM Length L Ch R = 1 ,9146.8  ,374.3,381.7,396.8
XS GIS Cut Line= 3
     1777637.652      435046.787     1777919.339      434922.972
     1778234.875       434644.01
#Sta/Elev= 30
       0 1026.46    29.8  1020.1    69.5 1013.41    79.4 1011.32    99.3 1006.33
     139  993.13   168.7  981.61   188.6  974.67   208.4  969.06   218.4   966.7
   228.3  965.72   238.2  960.82   248.1  958.97   258.1  958.52     268  955.83
   277.9  952.02   287.8  948.95   297.8  947.07   307.7  946.73   327.3  947.14
   337.1  948.56   346.9  949.22     386   949.9   425.2  952.47   444.8  955.84
   513.4   964.5   572.2  973.36   611.3  980.04   630.9  984.19   728.9 1011.72
#Mann= 3 , 0 , 0
       0     .08       0   297.8    .045       0   327.3    .055       0
Bank Sta=297.8,327.3
XS Rating Curve= 0 ,0
Exp/Cntr=0.3,0.1

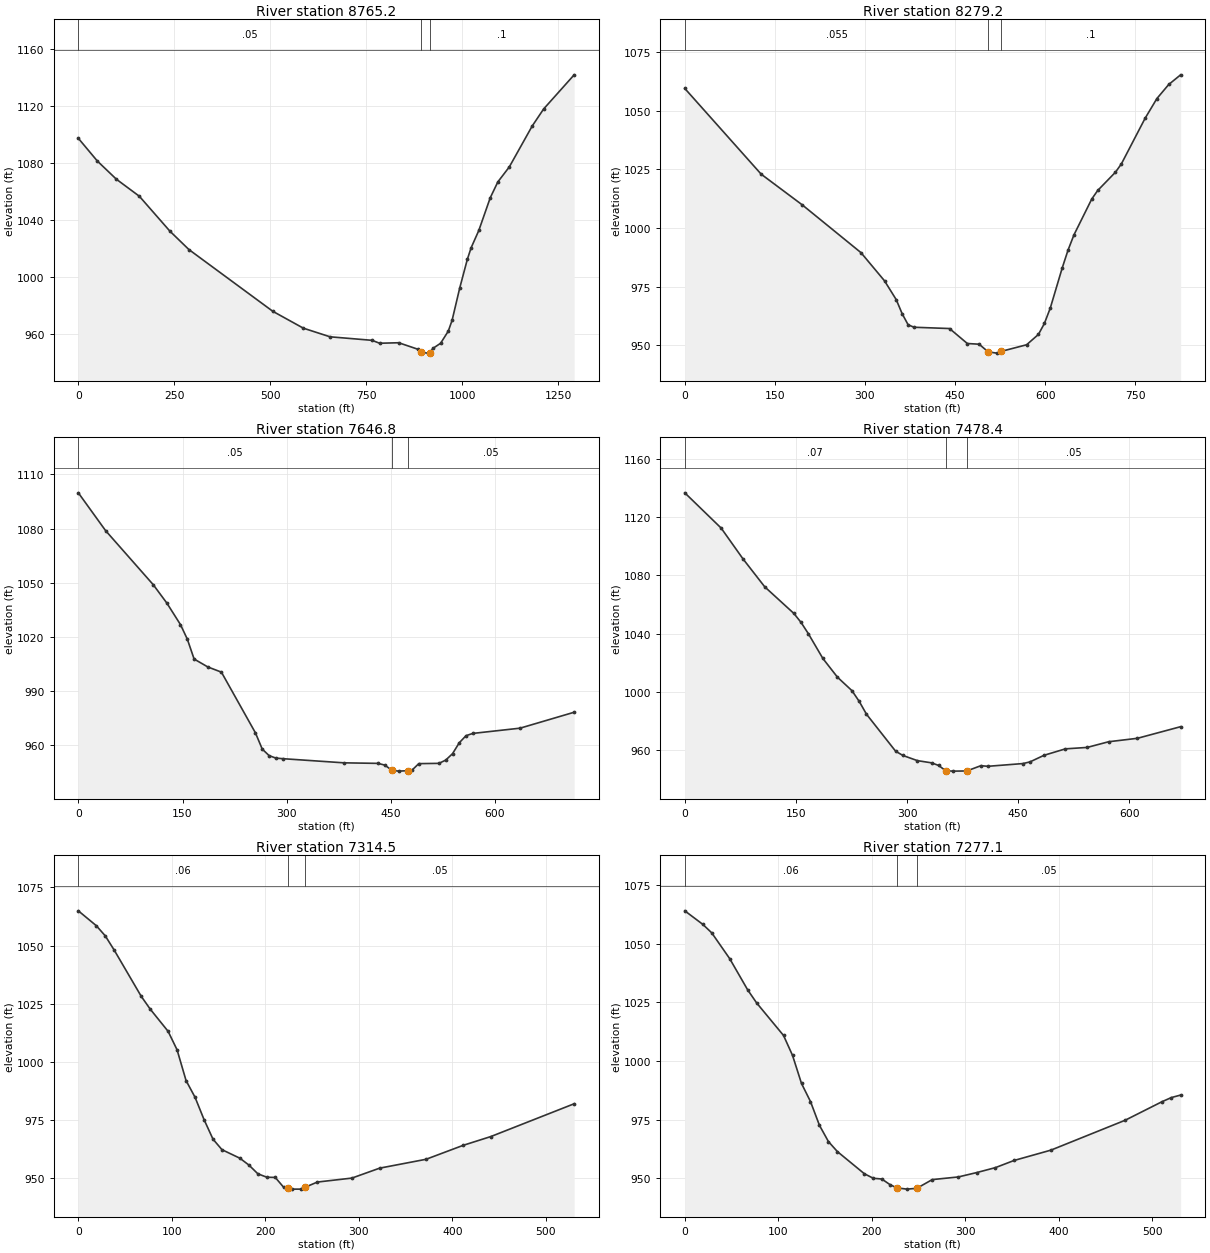
Type RM Length L Ch R = 1 ,8765.2  ,472.4,486,498.9
XS GIS Cut Line= 3
     1777294.669      435225.324     1778266.125      435164.843
     1778583.833       435175.26
#Sta/Elev= 30
       0 1097.14    49.7 1081.17    99.3 1068.45   158.9 1056.57   238.4 1032.15
     288 1019.24   506.5     976     586   964.2   655.5  958.16   764.8   955.7
   784.6  953.65   834.3     954     884  949.47  892.51947.3124   909.5  946.73
  914.66947.0535   923.7   950.1   943.5  953.66   963.4  962.13   973.3  969.68
   993.2  992.32  1013.1 1012.49    1023 1020.57  1042.9 1032.61  1072.7 1055.52
  1092.5 1066.62  1122.3  1077.1  1181.9 1105.73  1211.8 1117.71  1291.2 1141.59
#Mann= 3 , 0 , 0
       0     .05       0  892.51    .045       0  914.66      .1       0
Bank Sta=892.51,914.66
XS Rating Curve= 0 ,0
Exp/Cntr=0.3,0.1

Type RM Length L Ch R = 1 ,8279.2  ,648.6,632.3,613.1
XS GIS Cut Line= 3
     1777389.389      435295.051      1777719.25      435418.315
     1778130.708       435652.69
#Sta/Elev= 30
       0 1059.54   127.2    1023   195.6 1009.92   293.4  989.56   332.6  977.55
   352.1  969.53     362  963.51   371.9  958.81   381.7  957.76   440.9  957.21
   470.5  950.83   490.2  950.53  505.34 947.234   519.8  946.73  526.99947.4763
   569.2  950.29   588.9   954.7   598.8  959.36   608.6   965.9   628.4  982.93
   638.2  990.63   648.1  997.15   677.7 1012.41   687.6 1016.05   717.2 1023.85
     727 1027.37   766.5 1046.81   786.2 1055.24   805.9 1061.23   825.7 1065.35
#Mann= 3 , 0 , 0
       0    .055       0  505.34    .045       0  526.99      .1       0
Bank Sta=505.34,526.99
XS Rating Curve= 0 ,0
Exp/Cntr=0.3,0.1

Type RM Length L Ch R = 1 ,7646.8  ,185.6,168.5,152.8
XS GIS Cut Line= 3
     1777084.047      436029.729     1777539.822      435960.762
     1777782.618      435889.959
#Sta/Elev= 30
       0 1099.82    39.2 1078.92   107.9 1048.94   127.5 1038.76   147.1 1026.84
   156.9 1018.84   166.7 1007.81   186.4 1003.43     206 1000.55     255  966.94
   264.8  957.95   274.6  954.36   284.4  952.96   294.2  952.65   382.5  950.34
   431.5  950.04   441.4  949.07   451.2  946.28     461  945.75   475.2945.9959
   480.4  946.28   490.2   949.9   519.3  950.05     529  951.87   538.8  955.42
   548.5  961.46   558.2  965.37     568  966.63     636  969.53   713.9  978.35
#Mann= 3 , 0 , 0
       0     .05       0   451.2    .045       0   475.2     .05       0
Bank Sta=451.2,475.2
XS Rating Curve= 0 ,0
Exp/Cntr=0.3,0.1

Type RM Length L Ch R = 1 ,7478.4  ,176.4,163.9,152.4
XS GIS Cut Line= 4
     1777312.092      436388.034     1777537.786       436155.83
     1777650.634      436027.791     1777774.331      435904.093
#Sta/Elev= 30
       0 1136.86    49.1 1112.59    78.5 1091.45   107.9 1072.19   147.2 1053.89
     157 1047.66   166.8 1039.94   186.4 1022.89   206.1    1010   225.7 1000.72
   235.5  993.32   245.3  984.52   284.6  959.08   294.4  956.15     314  952.58
   333.3  951.05   342.8  949.24   352.3   945.6   361.7  945.36   380.7  945.47
   399.7   949.1   409.2  948.68   456.6  950.57     466  951.71     485  956.26
   513.9  960.69   543.1  961.66   572.2  965.58   611.1  967.95   669.4  975.94
#Mann= 3 , 0 , 0
       0     .07       0   352.3    .045       0   380.7     .05       0
Bank Sta=352.3,380.7
XS Rating Curve= 0 ,0
Exp/Cntr=0.3,0.1

Type RM Length L Ch R = 1 ,7314.5  ,37.4,37.4,37.4
XS GIS Cut Line= 4
     1777647.201      436383.014     1777716.646      436193.778
     1777730.534      436113.917     1777810.396      435879.542
#Sta/Elev= 30
       0 1064.94    19.2 1058.56    28.8 1054.19    38.4 1048.04    67.2 1028.24
    76.8 1022.74      96 1013.16   105.6  1005.2   115.2     992   124.8  984.83
   134.4  975.26     144  966.83   153.6  962.31   172.8  958.63   182.4   955.7
     192  951.94   201.6  950.47   210.6  950.38   219.6  946.13   223.8  945.77
   228.6  945.36   237.6  945.36  242.11946.0989   255.6   948.4   292.5   950.1
   322.2  954.37   371.8  958.18   411.4  964.16   441.1  967.95   530.2  982.04
#Mann= 3 , 0 , 0
       0     .06       0   223.8    .045       0  242.11     .05       0
Bank Sta=223.8,242.11
XS Rating Curve= 0 ,0
Exp/Cntr=0.3,0.1

Type RM Length L Ch R = 1 ,7277.1  ,100.7,99.2,97.7
XS GIS Cut Line= 4
     1777683.659      436391.695     1777753.104      436202.459
     1777766.993      436122.597     1777846.854      435888.222
#Sta/Elev= 30
       0 1063.96    19.2 1058.21    28.8 1054.58      48 1043.59    67.2  1030.3
    76.8 1024.72   105.6 1010.83   115.2 1002.35   124.8  990.38   134.4  982.69
     144  972.54   153.6  965.62   163.2  961.35     192  951.92   201.6  949.98
   210.6  949.68   219.6  947.23   226.9  945.89   237.6  945.36   248.1945.7067
   264.6  949.42   292.5  950.55   312.4  952.44   332.2  954.53     352  957.56
   391.6  961.99   470.8   974.7   510.4  982.64   520.3  984.38   530.2  985.45
#Mann= 3 , 0 , 0
       0     .06       0   226.9    .045       0   248.1     .05       0
Bank Sta=226.9,248.1
XS Rating Curve= 0 ,0
Exp/Cntr=0.3,0.1