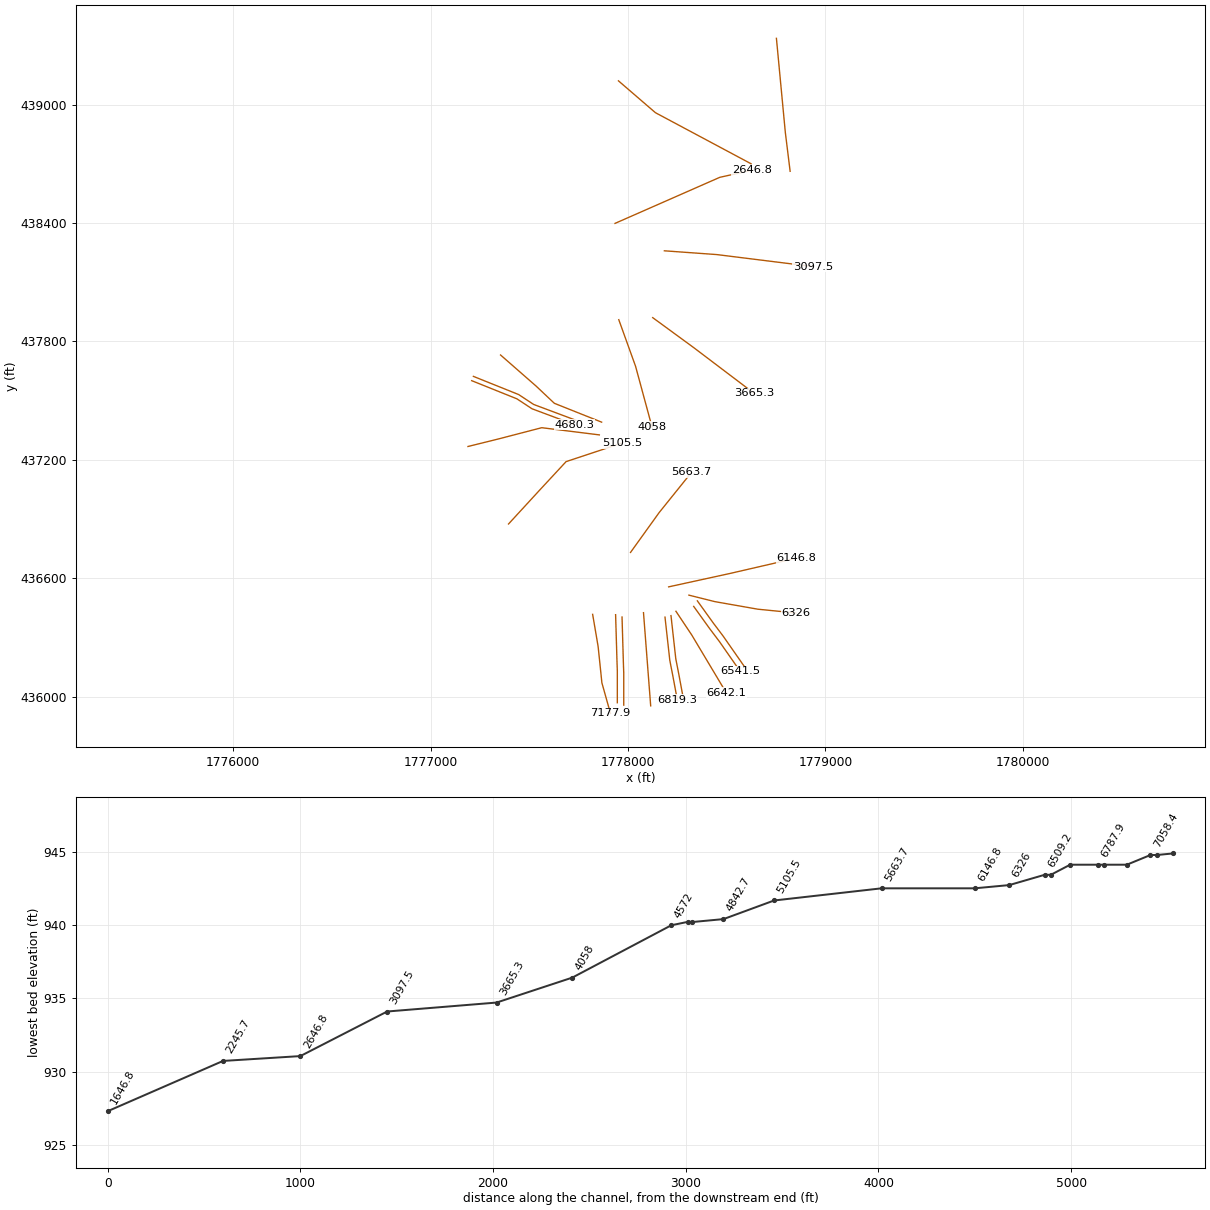
HEC-RAS study DaysRun.prj: DaysRun

--- DaysRun.g01 (geometry) --- (continued)

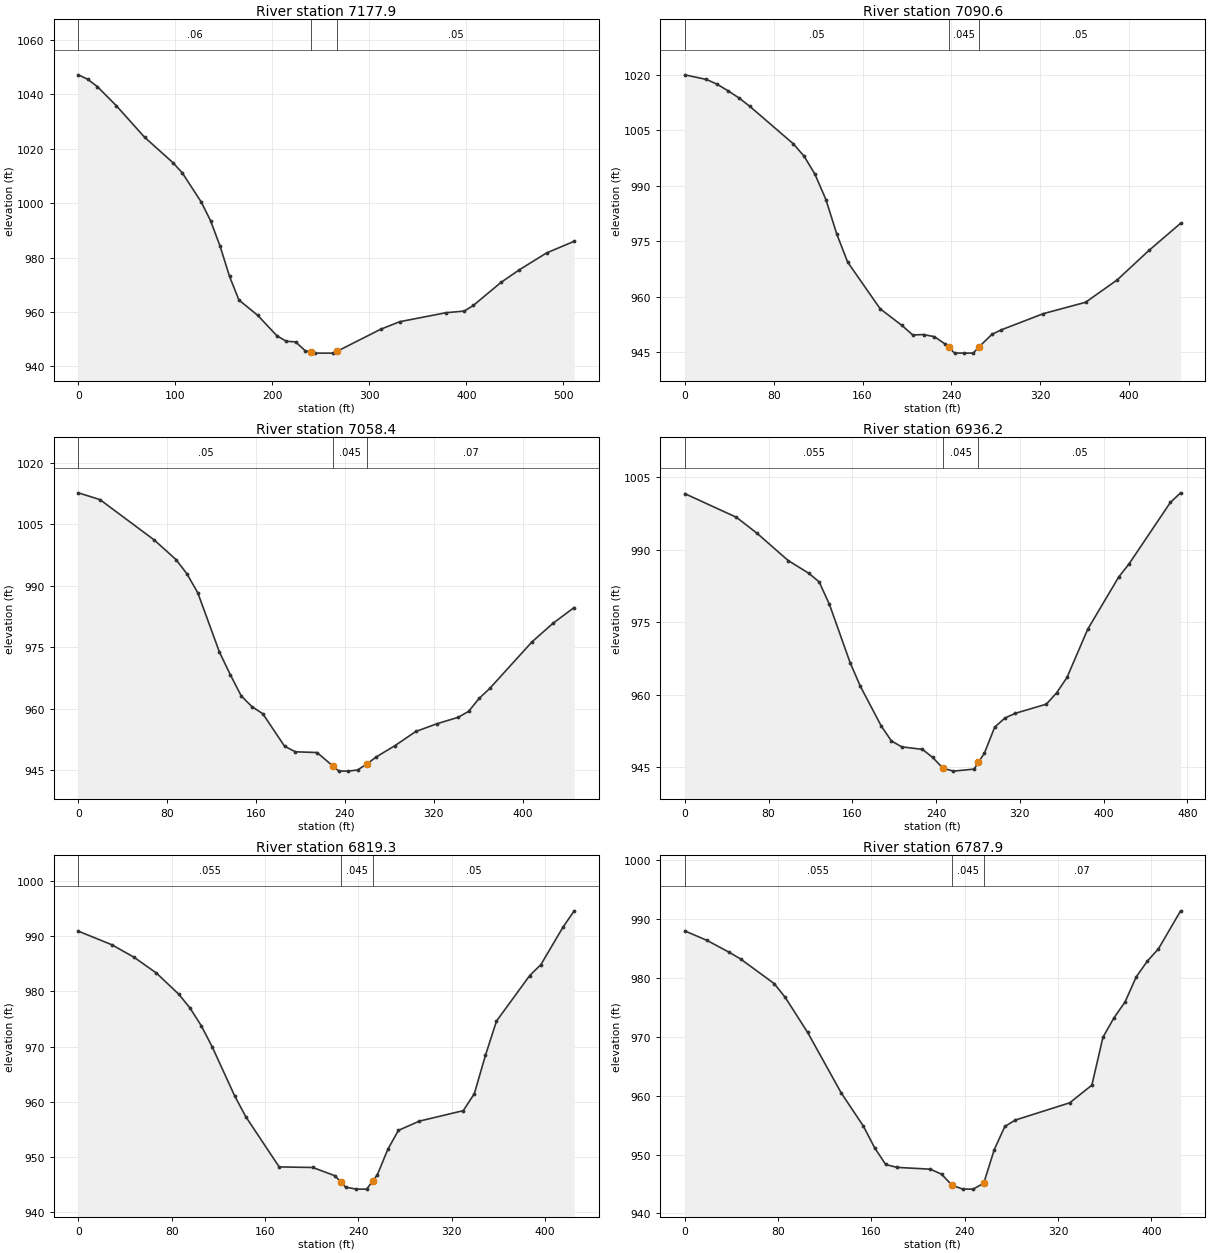
Type RM Length L Ch R = 1 ,7177.9  ,88.9,87.3,85.7
XS GIS Cut Line= 4
     1777820.812      436417.736      1777848.59      436254.542
     1777867.687      436070.514      1777911.09         435916.
#Sta/Elev= 30
       0 1047.13     9.7 1045.49    19.5 1042.84      39 1035.85    68.2 1024.24
    97.4 1014.89   107.1 1011.14   126.6 1000.44   136.3  993.52   146.1  984.17
   155.8  973.12   165.5   964.4     185  958.74   204.5  951.31   214.2  949.27
     224     949   233.7  945.81  239.38945.2713   243.4  944.89   262.9  944.89
  266.25945.4883   311.6  953.66   331.1  956.42   378.9  959.74   397.8  960.34
   407.2  962.44   435.5  970.84   454.4  975.48   482.7  981.72     511  985.97
#Mann= 3 , 0 , 0
       0     .06       0  239.38    .045       0  266.25     .05       0
Bank Sta=239.38,266.25
XS Rating Curve= 0 ,0
Exp/Cntr=0.3,0.1

Type RM Length L Ch R = 1 ,7090.6  ,32.3,32.2,32.2
XS GIS Cut Line= 4
     1777937.132         436416.     1777944.076      436181.625
     1777945.812      436131.278     1777945.812       435969.82
#Sta/Elev= 30
       0 1019.96    19.5 1018.71    29.3 1017.39    39.1 1015.61    48.8 1013.71
    58.6 1011.43    97.7 1001.32   107.5  997.94   117.2  993.08     127  986.28
   136.8  976.94   146.6  969.36   175.9  956.74   195.4  952.27   205.2  949.68
   214.9   949.8   224.7  949.22   234.5  947.21  237.48946.3483   242.8  944.81
   251.3  944.78   259.7   944.8  264.76946.4565   276.5  949.86   284.9  951.07
   322.8  955.45   360.8  958.52   389.3  964.58   417.8  972.53   446.3  979.86
#Mann= 3 , 0 , 0
       0     .05       0  237.48    .045       0  264.76     .05       0
Bank Sta=237.48,264.76
XS Rating Curve= 0 ,0
Exp/Cntr=0.3,0.1

Type RM Length L Ch R = 1 ,7058.4  ,121.1,122.2,123.1
XS GIS Cut Line= 4
     1777969.684      436404.065     1777976.628       436169.69
     1777978.364      436119.342     1777978.364      435957.884
#Sta/Elev= 30
       0 1012.73    19.5 1011.07    68.4  1001.2    87.9  996.44    97.7  992.97
   107.5  988.34     127  973.86   136.8  968.32   146.6  963.16   156.3  960.51
   166.1  958.78   185.6  950.87   195.4   949.5   214.9  949.32  229.14946.0204
   234.5   944.8   242.9  944.78   251.3  945.06   259.7   946.5   268.1  948.24
   284.9  950.99   303.8  954.46   322.8  956.35   341.8  957.91   351.3  959.37
   360.8  962.55   370.3  964.96   408.3  976.33   427.3  980.89   446.3  984.73
#Mann= 3 , 0 , 0
       0     .05       0  229.14    .045       0   259.7     .07       0
Bank Sta=229.14,259.7
XS Rating Curve= 0 ,0
Exp/Cntr=0.3,0.1

Type RM Length L Ch R = 1 ,6936.2  ,114.4,116.9,119.5
XS GIS Cut Line= 2
     1778078.408        436426.2     1778114.866      435953.978
#Sta/Elev= 30
       0 1001.64    49.3  996.74    69.1  993.41    98.7  987.78   118.4  985.14
   128.3  983.36   138.1  978.71   157.9  966.62   167.7  961.71   187.5  953.53
   197.3  950.39   207.2  949.15     227  948.63   236.8  946.95   246.7  944.71
   256.6  944.12   276.3  944.54  280.49945.9451   286.2  947.86     296  953.24
   305.9  955.15   315.8  956.11   345.4  958.01   355.2  960.36   365.1  963.55
   384.8  973.51   414.4  984.34   424.3  987.07   463.8  999.82   473.6 1001.81
#Mann= 3 , 0 , 0
       0    .055       0   246.7    .045       0  280.49     .05       0
Bank Sta=246.7,280.49
XS Rating Curve= 0 ,0
Exp/Cntr=0.3,0.1

Type RM Length L Ch R = 1 ,6819.3  ,31.3,31.5,31.5
XS GIS Cut Line= 4
     1778187.349       436403.63     1778211.654       436184.88
     1778227.279      436105.019     1778249.849      435983.492
#Sta/Elev= 30
       0  990.93    28.7  988.47    47.8  986.19      67  983.32    86.1  979.49
    95.7     977   105.3  973.81   114.8  969.93     134  961.06   143.5  957.29
   172.2  948.15     201  948.05   220.1  946.54  225.03945.4171   229.1  944.49
   238.2  944.12   247.2  944.12  252.29945.5599   256.3  946.69   265.3  951.32
   274.4  954.78   292.4  956.46     330  958.36   339.5  961.43     349  968.37
   358.5  974.61     387  982.88   396.6  984.87   415.6  991.68   425.1  994.62
#Mann= 3 , 0 , 0
       0    .055       0  225.03    .045       0  252.29     .05       0
Bank Sta=225.03,252.29
XS Rating Curve= 0 ,0
Exp/Cntr=0.3,0.1

Type RM Length L Ch R = 1 ,6787.9  ,137.5,145.8,153.6
XS GIS Cut Line= 4
     1778217.731      436411.226     1778242.036      436192.476
     1778257.661      436112.615     1778280.231      435991.087
#Sta/Elev= 30
       0  988.01    19.1  986.39    38.3  984.35    47.8  983.24    76.6  979.06
    86.1  976.71   105.3  970.76     134  960.51   153.1  954.83   162.7  951.17
   172.2  948.31   181.8  947.82   210.5  947.51   220.1  946.66   229.1  944.79
   238.2  944.13   247.2  944.12   256.3  945.12   265.3  950.82   274.4  954.78
   283.4  955.86     330  958.79     349  961.79   358.5  969.93     368  973.25
   377.5  975.94     387  980.19   396.6  982.88   406.1  984.97   425.1  991.42
#Mann= 3 , 0 , 0
       0    .055       0   229.1    .045       0   256.3     .07       0
Bank Sta=229.1,256.3
XS Rating Curve= 0 ,0
Exp/Cntr=0.3,0.1

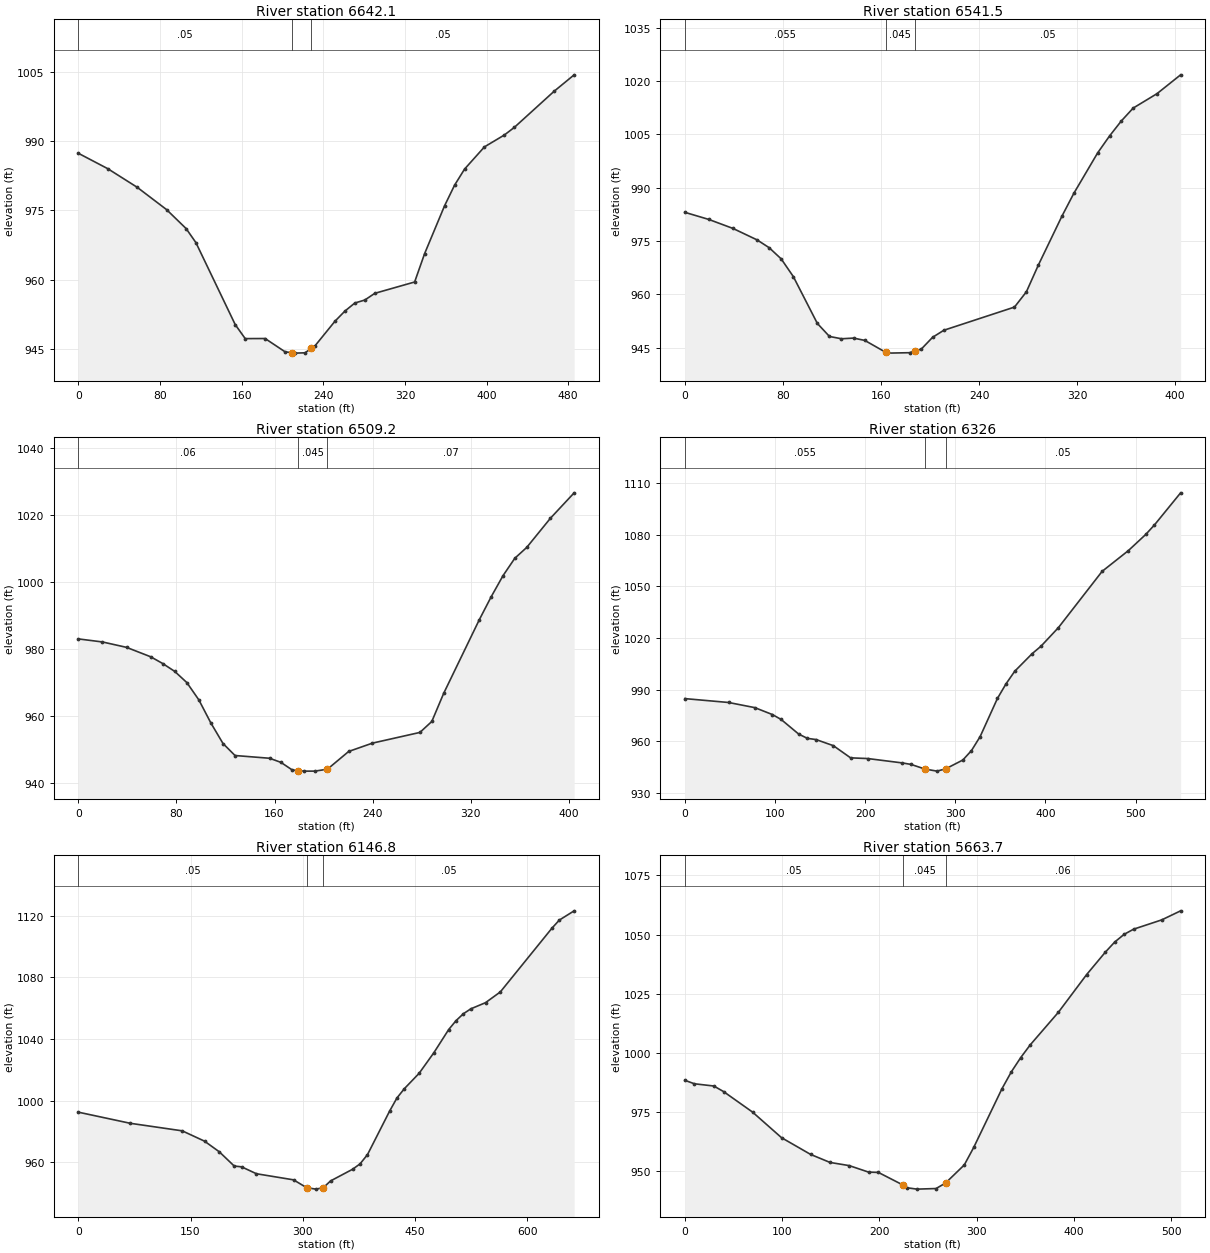
Type RM Length L Ch R = 1 ,6642.1  ,98.3,100.6,103.3
XS GIS Cut Line= 3
     1778242.687      436433.361     1778322.548       436313.57
     1778497.896      436020.167
#Sta/Elev= 30
       0  987.36    28.8  984.03    57.6  980.01    86.4  975.18   105.6  971.07
   115.2  968.03   153.7   950.3   163.5  947.26     183  947.28   202.6   944.4
   209.3  944.21   212.3  944.12   222.1  944.19  228.18945.1273   231.9   945.7
   251.4  951.01   261.2  953.22   270.9  954.96   280.7  955.61   290.5  957.06
   329.5  959.51   339.3  965.66   358.8  975.98   368.6  980.44   378.4  983.93
   397.9  988.74   417.4  991.31   427.2  992.96   466.2 1000.78   485.8 1004.33
#Mann= 3 , 0 , 0
       0     .05       0   209.3    .045       0  228.18     .05       0
Bank Sta=209.3,228.18
XS Rating Curve= 0 ,0
Exp/Cntr=0.3,0.1

Type RM Length L Ch R = 1 ,6541.5  ,32.3,32.4,32.5
XS GIS Cut Line= 4
      1778332.82      436457.812     1778413.115      436346.049
     1778463.029       436279.86      1778568.28      436129.036
#Sta/Elev= 30
       0  983.06    19.7  981.04    39.3  978.52      59  975.29    68.8   973.1
    78.6  969.96    88.5  964.98   108.1  951.79     118  948.12   127.8  947.47
   137.6  947.66   146.8  947.01  163.84943.6636   165.2  943.43   183.3  943.55
  187.56943.9838   192.9  944.57   202.1  947.88   211.3  949.87   268.9  956.39
   278.6  960.68   288.3  968.16   307.6  981.98   317.3   988.4   336.7  999.77
   346.4 1004.53     356 1008.75   365.7 1012.39   385.1 1016.44   404.4 1021.75
#Mann= 3 , 0 , 0
       0    .055       0  163.84    .045       0  187.56     .05       0
Bank Sta=163.84,187.56
XS Rating Curve= 0 ,0
Exp/Cntr=0.3,0.1

Type RM Length L Ch R = 1 ,6509.2  ,166.1,183.2,199.9
XS GIS Cut Line= 4
     1778351.266      436486.023     1778431.562      436374.261
     1778481.475      436308.072     1778586.727      436157.247
#Sta/Elev= 30
       0  982.89    19.7  981.98    39.3  980.37      59  977.56    68.8  975.55
    78.6   973.2    88.5  969.86    98.3  964.69   108.1   957.8     118  951.67
   127.8  948.09     156  947.27   165.2  946.05   174.5  943.77  179.36943.5904
   183.7  943.43   192.9  943.43  203.15943.9999   220.5   949.3   239.9  951.79
   278.6  954.98   288.3  958.25     298  966.66     327  988.59   336.7  995.45
   346.4 1001.78     356 1006.96   365.7 1010.19   385.1 1018.93   404.4 1026.49
#Mann= 3 , 0 , 0
       0     .06       0  179.36    .045       0  203.15     .07       0
Bank Sta=179.36,203.15
XS Rating Curve= 0 ,0
Exp/Cntr=0.3,0.1

Type RM Length L Ch R = 1 ,6326    ,170.2,179.1,188.4
XS GIS Cut Line= 4
     1778308.659      436514.959     1778440.604      436481.972
     1778657.618      436443.778     1778850.326      436424.681
#Sta/Elev= 30
       0  984.81    48.6  982.56    77.7  979.57    97.2  975.55   106.9   972.7
   126.3  964.24     136  961.74   145.6  961.05   164.8   957.5   183.9  950.44
   203.1  950.02   241.4  947.48     251  946.62  266.32 943.948   279.7  942.73
   289.3  944.04   308.4  949.17     318  954.65   327.6  962.76   346.8  984.92
   356.4  993.45     366  1000.7   385.4 1010.94   395.1 1015.21   414.4 1025.98
   462.9 1058.64   491.9 1070.63   511.3 1080.06     521  1085.6     550 1104.22
#Mann= 3 , 0 , 0
       0    .055       0  266.32    .045       0   289.3     .05       0
Bank Sta=266.32,289.3
XS Rating Curve= 0 ,0
Exp/Cntr=0.3,0.1

Type RM Length L Ch R = 1 ,6146.8  ,466.5,483.1,499.1
XS GIS Cut Line= 3
     1778205.867      436556.915     1778516.042      436624.661
     1778852.569      436702.314
#Sta/Elev= 30
       0  992.48    69.4  985.26   138.9  980.36   168.7  973.66   188.5  966.73
   208.4  957.51   218.3  956.98   238.1   952.5   287.7  948.54  305.29943.4484
   317.5  942.51   327.4   943.4   337.2  947.83   366.8  955.44   376.7  958.95
   386.6  964.92   416.2  993.21     426 1001.72   435.9 1007.74   455.6  1017.7
   475.4 1031.13   495.1  1046.1     505 1051.92   514.8 1056.39   524.7 1059.57
   544.4 1063.58   564.2 1070.56   633.2 1111.95   643.1 1117.22   662.9 1123.22
#Mann= 3 , 0 , 0
       0     .05       0  305.29    .045       0   327.4     .05       0
Bank Sta=305.29,327.4
XS Rating Curve= 0 ,0
Exp/Cntr=0.3,0.1

Type RM Length L Ch R = 1 ,5663.7  ,561,558.2,555.7
XS GIS Cut Line= 3
     1778012.671      436731.321      1778157.69      436933.217
     1778321.264      437136.486
#Sta/Elev= 30
       0  988.49     9.9  987.01    29.8  986.07    39.8  983.73    69.6  975.06
    99.4  964.24   129.3  957.17   149.2  953.79     169  952.44   188.9  949.69
   198.9  949.57   224.7  944.14   228.7  943.06   238.6  942.51   258.2  942.76
   267.9  945.07   287.2  952.73   296.9  960.13   325.9  984.91   335.6  992.09
   345.2  998.08   354.9 1003.42   383.9 1017.22   412.9 1033.13   432.2 1042.64
   441.8  1046.9   451.5 1050.15   461.2 1052.32   490.2 1056.26   509.5 1060.07
#Mann= 3 , 0 , 0
       0     .05       0   224.7    .045       0   267.9     .06       0
Bank Sta=224.7,267.9
XS Rating Curve= 0 ,0
Exp/Cntr=0.3,0.1

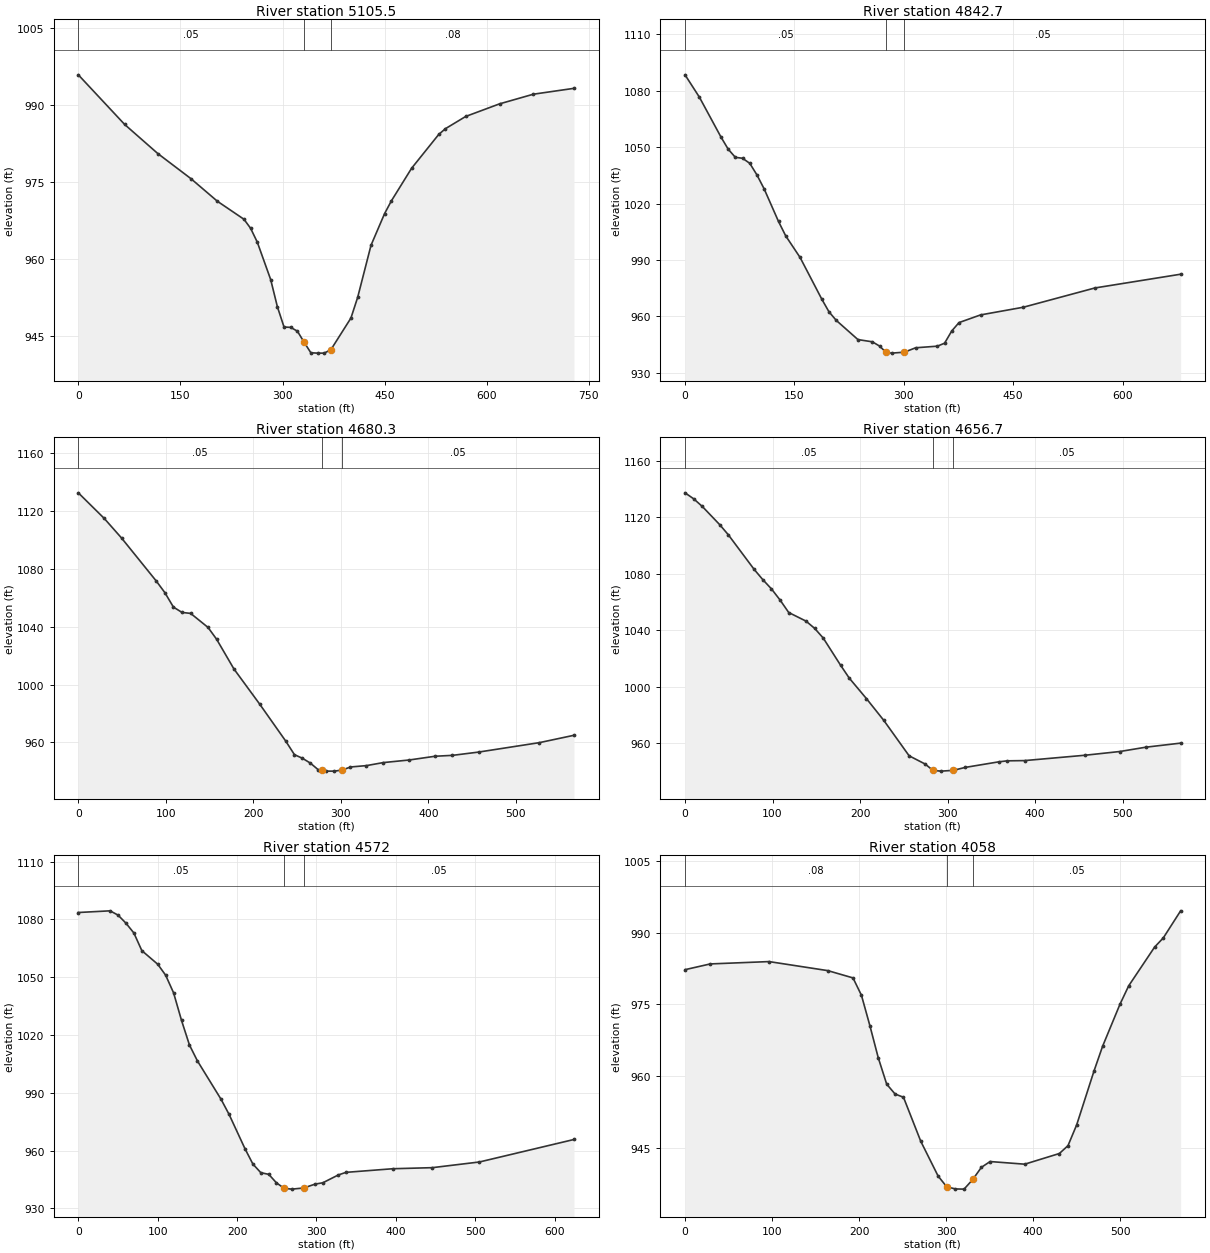
Type RM Length L Ch R = 1 ,5105.5  ,276,262.9,249.7
XS GIS Cut Line= 4
     1777394.615      436875.419     1777552.601      437047.294
     1777686.282      437191.391     1777969.268      437285.141
#Sta/Elev= 30
       0  995.83    68.1  986.17   116.7  980.52   165.4  975.63   204.3  971.23
   243.3  967.73   253.1  965.97   262.9  963.28   282.6  955.99   292.4  950.72
   302.2  946.76   312.1  946.69   321.9  945.94   331.7   943.8   341.6  941.75
   351.4  941.68   361.2  941.68     371  942.34   400.5  948.51   410.4  952.54
     430  962.67   449.9  968.82   459.8  971.28   489.6  977.65   529.4  984.22
   539.3  985.35   569.1  987.73   618.8  990.18   668.5  992.06   728.1   993.2
#Mann= 3 , 0 , 0
       0     .05       0   331.7    .045       0     371     .08       0
Bank Sta=331.7,371
XS Rating Curve= 0 ,0
Exp/Cntr=0.3,0.1

Type RM Length L Ch R = 1 ,4842.7  ,181.9,162.3,142.6
XS GIS Cut Line= 4
      1777189.32      437268.069     1777342.532      437305.974
     1777563.018      437363.266     1777854.684      437326.808
#Sta/Elev= 30
       0 1088.49    19.7 1076.61    49.3 1055.39    59.2 1048.93      69 1044.59
    78.9 1044.09    88.8  1041.4    98.6 1035.24   108.5 1027.81   128.2 1010.46
   138.1 1002.78   157.8   991.3   187.6  969.08   197.4   962.4   207.4  957.83
   237.1  947.62   256.9  946.43   266.8  944.16  275.62 940.828   283.3  940.41
  300.76940.9134   316.3  943.26     346  944.11   355.9  945.69   365.8  952.23
   375.7  956.66   405.2  960.74     464  964.84     562  975.08   679.6   982.4
#Mann= 3 , 0 , 0
       0     .05       0  275.62    .045       0  300.76     .05       0
Bank Sta=275.62,300.76
XS Rating Curve= 0 ,0
Exp/Cntr=0.3,0.1

Type RM Length L Ch R = 1 ,4680.3  ,23.4,23.6,23.8
XS GIS Cut Line= 4
     1777207.983      437601.547      1777437.15      437509.533
     1777513.539      437459.186      1777727.08      437379.325
#Sta/Elev= 30
       0  1132.4    29.6 1114.73    49.4 1101.19    88.9 1071.63    98.8 1063.56
   108.7 1053.48   118.5 1049.81   128.4 1049.13   148.2 1039.47     158 1031.33
   177.8  1010.8   207.4  986.37   237.1   960.9     247  951.57   256.1   949.1
   265.2  945.74   274.4  941.05     278  940.72   283.5  940.21   292.7  940.21
   301.8     941     311  943.07   329.3  944.02   348.4   946.1   378.1   947.9
   407.8  950.49   427.6   951.1   457.4  953.36   526.8  959.87   566.4  964.96
#Mann= 3 , 0 , 0
       0     .05       0     278    .045       0   301.8     .05       0
Bank Sta=278,301.8
XS Rating Curve= 0 ,0
Exp/Cntr=0.3,0.1

Type RM Length L Ch R = 1 ,4656.7  ,88.8,84.7,80.6
XS GIS Cut Line= 4
     1777216.664      437623.249      1777445.83      437531.235
     1777522.219      437480.887     1777735.761      437401.026
#Sta/Elev= 30
       0 1137.35     9.9 1133.11    19.8 1127.67    39.5 1114.89    49.4  1107.7
      79 1083.13    88.9 1075.85    98.8 1069.29   108.7 1061.36   118.5 1052.58
   138.3 1046.47   148.2 1041.31     158 1034.44   177.8 1015.22   187.7  1006.1
   207.4  991.54   227.2  976.13   256.1  951.08   274.4  945.25   283.5  940.68
   292.7  940.22   306.6  940.76   320.1  942.84   358.3  946.78   368.2  947.51
     388  947.68   457.4  951.49     497  954.12   526.8  957.19   566.4  960.06
#Mann= 3 , 0 , 0
       0     .05       0   283.5    .045       0   306.6     .05       0
Bank Sta=283.5,306.6
XS Rating Curve= 0 ,0
Exp/Cntr=0.3,0.1

Type RM Length L Ch R = 1 ,4572    ,525.7,514,502.3
XS GIS Cut Line= 4
      1777354.25      437731.611     1777534.806      437573.625
      1777626.82      437486.819     1777866.403      437391.333
#Sta/Elev= 30
       0 1083.61      40 1084.48      50 1082.26      60 1078.08      70 1072.96
      80 1063.82     100 1056.76     110 1051.06     120 1041.89     130 1027.58
     140 1014.81     150 1006.58   179.9  986.56   189.9  978.79   209.9     961
   219.9  953.01   229.9  948.52   239.9  947.66   249.6  943.24   259.4  940.38
   269.1  939.99  283.91940.5907   298.3   942.6     308  943.29   327.5  947.35
   337.2   948.7   396.2  950.58   445.8  951.13   505.3  954.09   624.3  965.76
#Mann= 3 , 0 , 0
       0     .05       0   259.4    .045       0  283.91     .05       0
Bank Sta=259.4,283.91
XS Rating Curve= 0 ,0
Exp/Cntr=0.3,0.1

Type RM Length L Ch R = 1 ,4058    ,378.6,392.8,406.9
XS GIS Cut Line= 3
     1777953.209       437910.43     1778038.278      437674.319
     1778121.612      437367.027
#Sta/Elev= 30
       0  982.25      29  983.45    96.5  983.94   164.1  982.05     193  980.53
   202.7   976.9   212.4  970.55     222  963.86   231.7  958.34   241.3  956.29
     251   955.6   270.9  946.39   290.8  939.14   300.7   936.9   310.7  936.46
   320.6  936.42   330.6  938.44   340.5  940.97   350.5  942.18   390.3  941.63
   430.1  943.86     440   945.5     450  949.86   469.9   961.1   479.8  966.28
   499.7  975.03   509.7  978.87   539.5  986.97   549.5  988.89   569.4  994.54
#Mann= 3 , 0 , 0
       0     .08       0   300.7    .045       0   330.6     .05       0
Bank Sta=300.7,330.6
XS Rating Curve= 0 ,0
Exp/Cntr=0.3,0.1

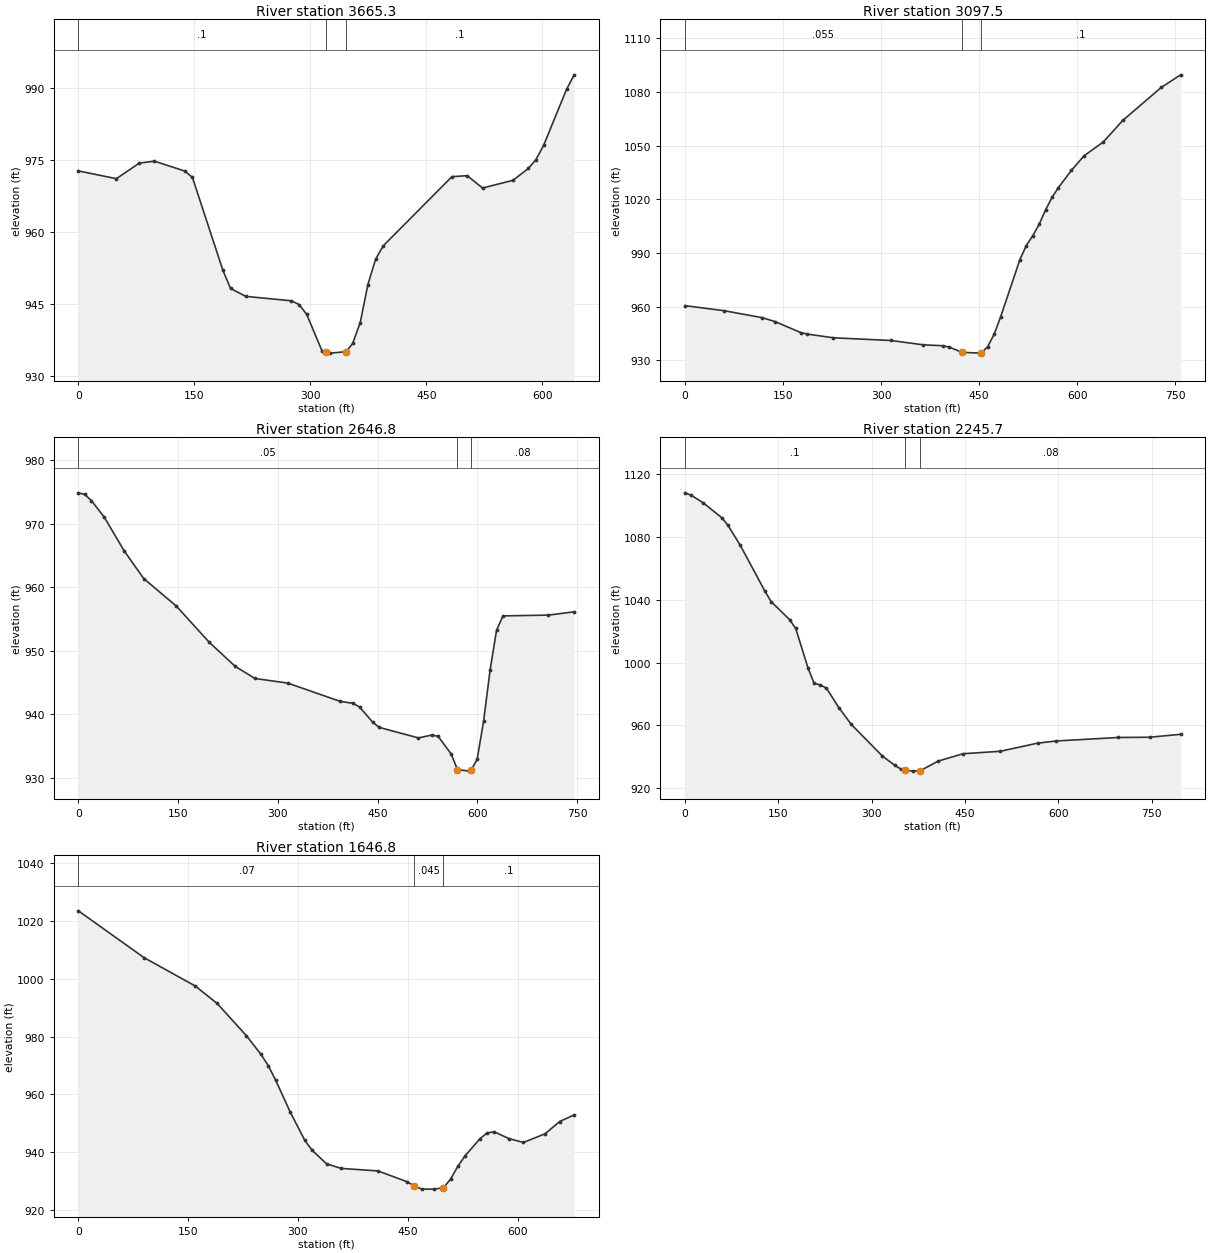
Type RM Length L Ch R = 1 ,3665.3  ,555.8,567.8,579.5
XS GIS Cut Line= 3
     1778125.084      437920.847     1778331.681      437769.805
     1778638.973      437537.166
#Sta/Elev= 30
       0  972.76    49.2  971.13    78.8  974.38    98.4  974.79   137.8  972.72
   147.6  971.38     187     952   196.9  948.22   216.6  946.57   275.7  945.64
   285.6  944.85   295.4   942.8   315.2  935.18  320.07934.9537   325.1  934.72
   346.3  935.01   354.8  936.73   364.6  941.09   374.5  949.01   384.4  954.28
   394.3  957.11   483.2  971.55     503  971.76   522.8  969.18   562.3   970.8
     582  973.26   591.9  975.11   601.8  978.09   631.5  989.79   641.3  992.81
#Mann= 3 , 0 , 0
       0      .1       0  320.07    .045       0   346.3      .1       0
Bank Sta=320.07,346.3
XS Rating Curve= 0 ,0
Exp/Cntr=0.3,0.1

Type RM Length L Ch R = 1 ,3097.5  ,438.5,450.6,457.1
XS GIS Cut Line= 3
     1778184.112      438259.389     1778449.737      438240.291
     1778937.584      438179.527
#Sta/Elev= 30
       0  960.63    59.2  957.87   118.4  953.92   138.1  951.71   177.5  945.56
   187.4  944.75   226.9  942.69   315.5  941.17   364.6  938.74   394.1  938.25
     404  937.52   423.6  934.54   453.1  934.11  453.36934.2058     463  937.76
   472.8   944.6   482.6  954.22   512.1  986.21     522  994.24   531.8  999.64
   541.6 1006.07   551.4 1014.08   561.3  1021.1   571.1 1026.62   590.8 1036.16
   610.4  1044.4   639.9 1052.16   669.4 1064.13   728.4  1082.6   757.9 1089.62
#Mann= 3 , 0 , 0
       0    .055       0   423.6    .045       0  453.36      .1       0
Bank Sta=423.6,453.36
XS Rating Curve= 0 ,0
Exp/Cntr=0.3,0.1

Type RM Length L Ch R = 1 ,2646.8  ,423.2,401.1,384.8
XS GIS Cut Line= 3
     1777934.112      438398.277     1778465.327      438631.793
      1778626.82      438667.375
#Sta/Elev= 30
       0   974.9     9.8  974.64    19.7  973.67    39.3  971.02    68.8  965.78
    98.4  961.39   147.5  957.05   196.7  951.38     236  947.56   265.6  945.66
   314.7  944.94   393.4  942.07   413.1  941.74   422.9  941.17   442.6  938.79
   452.4  937.96   511.4   936.3   531.1  936.74   540.9  936.57   560.6  933.78
  570.14931.3171   587.8  931.07  591.14931.2886   599.7  932.93   609.5  938.99
   619.2  946.99   628.9  953.26   638.6  955.52   706.7  955.64   745.6  956.16
#Mann= 3 , 0 , 0
       0     .05       0  570.14    .045       0  591.14     .08       0
Bank Sta=570.14,591.14
XS Rating Curve= 0 ,0
Exp/Cntr=0.3,0.1

Type RM Length L Ch R = 1 ,2245.7  ,620.9,598.9,577.8
XS GIS Cut Line= 3
     1777951.473        439120.5     1778138.973      438959.041
     1778623.348      438700.361
#Sta/Elev= 30
       0 1108.29     9.9 1106.84    29.7 1101.88    59.4 1092.43    69.3  1087.6
    89.1 1074.81   128.7 1045.58   138.6 1038.95   168.3 1027.43   178.2 1021.75
     198   996.5   207.8  986.75   217.7  985.77   227.6  983.67   247.4  971.33
   267.4  960.58   317.3  940.41   337.3  934.48   347.3  931.99     354   931.2
   367.2  930.74  378.58931.0815   407.2  937.16   447.1  941.84     507  943.41
   566.9   948.6   596.9  949.98   696.7  952.21   746.6  952.35   796.6  954.23
#Mann= 3 , 0 , 0
       0      .1       0     354    .045       0  378.58     .08       0
Bank Sta=354,378.58
XS Rating Curve= 0 ,0
Exp/Cntr=0.3,0.1

Type RM Length L Ch R = 1 ,1646.8  ,542.5,556.1,568.4
XS GIS Cut Line= 3
      1778751.82      439335.777     1778796.974      438859.007
     1778821.264      438662.166
#Sta/Elev= 30
       0  1023.4    89.8 1007.23   159.6  997.46   189.6  991.42   229.5   980.3
   249.4  973.86   259.4  969.96   269.4  964.98   289.3  953.97   309.3  944.16
   319.3  940.73   339.2  936.02   359.2  934.46   409.1   933.6     449  929.87
     459  928.35   468.9  927.32   486.4  927.31   498.7  927.81   508.6  930.83
   518.6   935.3   528.5  938.89   548.3  944.66   558.2  946.71   568.2   947.1
     588  944.77   607.8  943.42   637.6  946.44   657.4  950.66   677.2  952.93
#Mann= 3 , 0 , 0
       0     .07       0     459    .045       0   498.7      .1       0
Bank Sta=459,498.7
XS Rating Curve= 0 ,0
Exp/Cntr=0.3,0.1