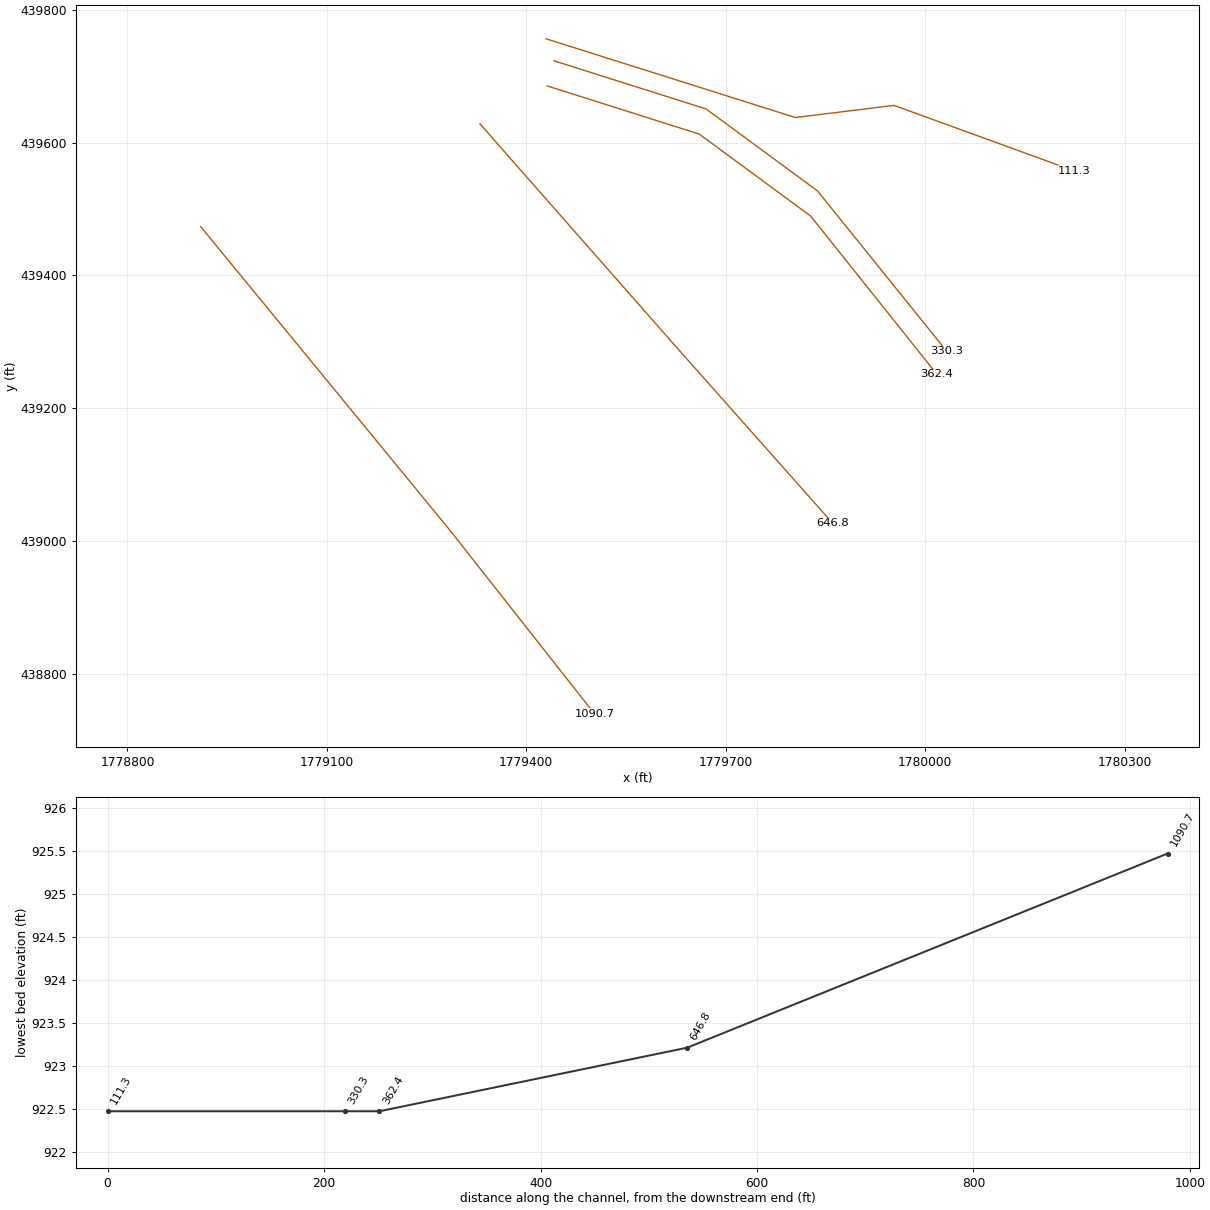
HEC-RAS study DaysRun.prj: DaysRun

--- DaysRun.g01 (geometry) --- (continued)

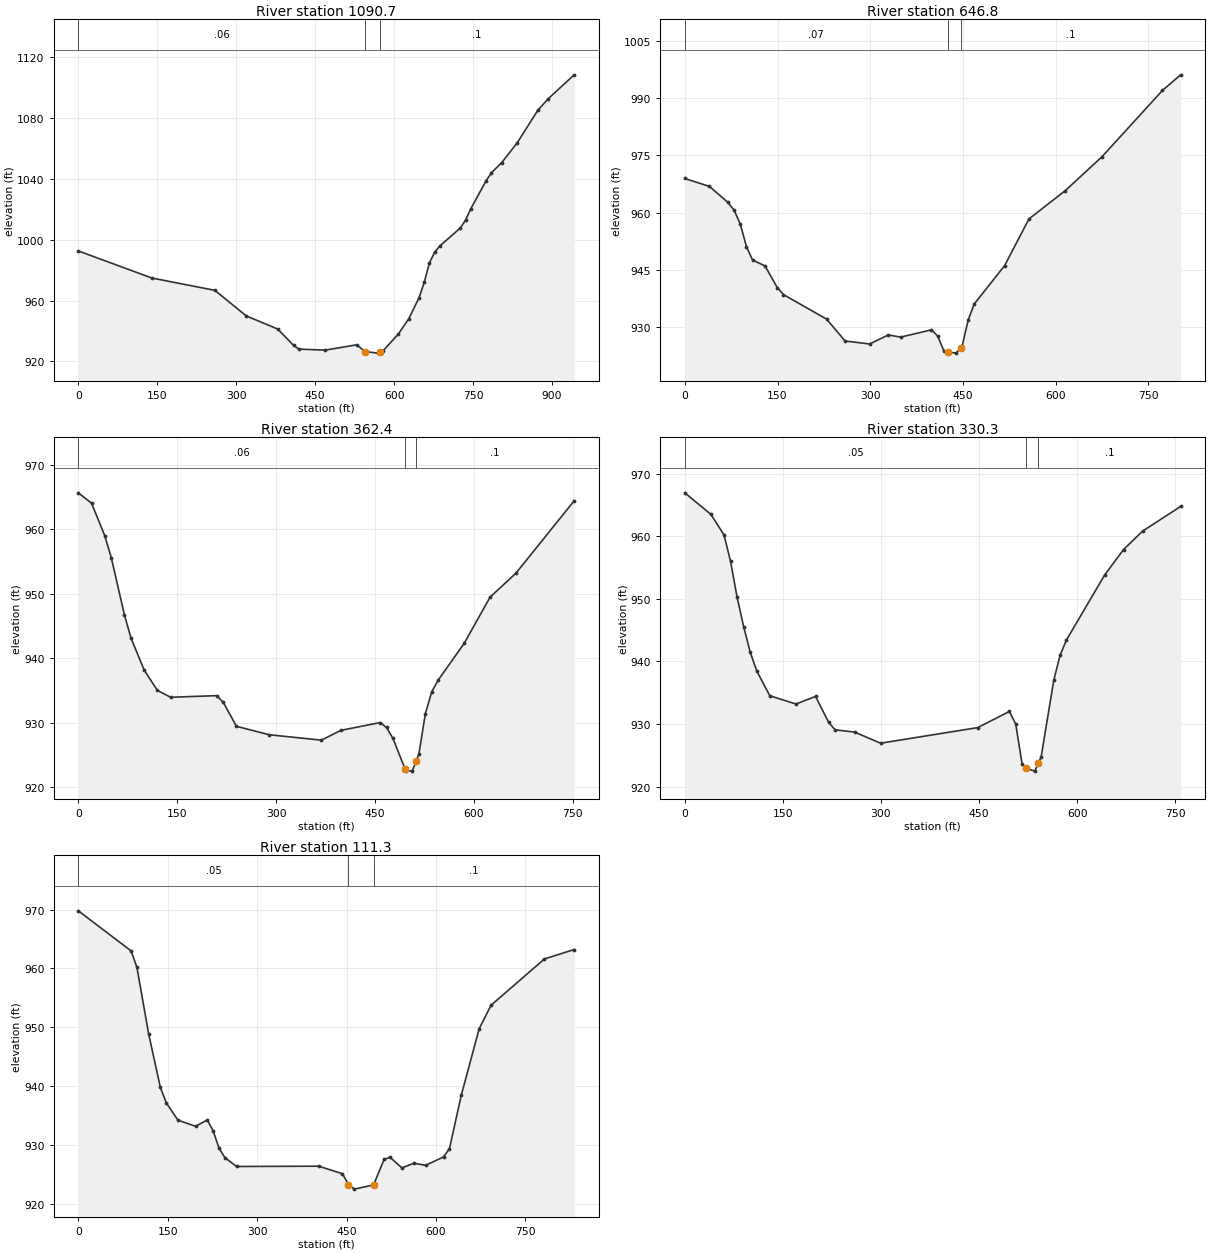
Type RM Length L Ch R = 1 ,1090.7  ,442.7,443.9,445.2
XS GIS Cut Line= 3
      1778910.24      439473.364     1779283.504      439018.503
     1779502.254      438740.725
#Sta/Elev= 30
       0  992.59   139.6  974.81   259.3  966.73   319.1  949.91     379  941.25
   408.9  930.56   418.9  928.12   468.7  927.43   528.6  930.92  545.32926.4894
   568.4  925.47  573.76926.1614   578.4  926.76     608  938.04   627.7     948
   647.3  961.85   657.2  972.03     667  984.74   676.8  991.66   686.6  995.81
   725.9 1007.72   735.7 1012.89   745.6 1020.28     775 1038.86   784.8 1043.93
   804.5 1050.69   833.9 1063.67   873.2 1085.11   892.9 1092.63     942 1108.29
#Mann= 3 , 0 , 0
       0     .06       0  545.32    .045       0  573.76      .1       0
Bank Sta=545.32,573.76
XS Rating Curve= 0 ,0
Exp/Cntr=0.3,0.1

Type RM Length L Ch R = 1 ,646.8   ,285.8,284.4,282.9
XS GIS Cut Line= 3
     1779330.321      439628.052      1779620.15      439298.456
     1779861.195       439026.75
#Sta/Elev= 30
       0  968.94    39.9  966.86    69.8  962.67    79.8  960.63    89.8  956.99
    99.8  951.07   109.7  947.57   129.7  946.05   149.6  940.38   159.6  938.54
   229.4  932.11   259.4  926.38   299.2  925.61   329.2  927.97   349.1   927.4
     399  929.31     409  927.69     419  923.87  425.08923.5138   438.9  923.21
   446.4  924.63   448.7  925.07   458.5  931.95   468.4  936.11   517.4  946.13
   556.7  958.34   615.6  965.77   674.5  974.57   772.7  991.99   802.1  996.08
#Mann= 3 , 0 , 0
       0     .07       0  425.08    .045       0   446.4      .1       0
Bank Sta=425.08,446.4
XS Rating Curve= 0 ,0
Exp/Cntr=0.3,0.1

Type RM Length L Ch R = 1 ,362.4   ,32,32.1,32.2
XS GIS Cut Line= 4
     1779431.363       439685.17     1779660.095      439612.687
      1779827.63      439489.423     1780017.474      439251.489
#Sta/Elev= 30
       0  965.68      20  964.08      40  959.05      50  955.61      70   946.7
      80   943.1     100  938.14     120     935     140  933.94     210  934.19
     220  933.13   239.9  929.43   289.5  928.12   368.7  927.28   398.4   928.8
   457.8  930.01   467.6  929.25   477.4  927.54  495.48922.8546     497  922.47
   506.8  922.54   512.5  924.01   516.7  925.09   526.5  931.38   536.3  934.81
   546.1  936.62   585.4   942.3   624.7  949.48     664  953.21   752.3  964.44
#Mann= 3 , 0 , 0
       0     .06       0  495.48    .045       0   512.5      .1       0
Bank Sta=495.48,512.5
XS Rating Curve= 0 ,0
Exp/Cntr=0.3,0.1

Type RM Length L Ch R = 1 ,330.3   ,195.3,219,242.2
XS GIS Cut Line= 4
     1779441.779       439722.93     1779670.512      439650.448
     1779838.047      439527.184     1780032.752      439285.517
#Sta/Elev= 30
       0  966.92      40  963.47      60  960.19      70  955.97      80  950.24
      90  945.55     100  941.48     110  938.48     130  934.51     170  933.19
     200   934.4     220  930.26   229.9  929.07   259.8   928.7   299.4  926.93
   447.9  929.42   496.4     932   506.1  929.99   515.8  923.64   521.8  922.93
   535.2  922.47  540.73923.7376   544.9  924.69   564.3  936.98     574     941
   583.7  943.42   641.9  953.76     671  957.86   700.1   960.8   758.3  964.74
#Mann= 3 , 0 , 0
       0     .05       0   521.8    .045       0  540.73      .1       0
Bank Sta=521.8,540.73
XS Rating Curve= 0 ,0
Exp/Cntr=0.3,0.1

Type RM Length L Ch R = 1 ,111.3   ,112.9,111.3,110.2
XS GIS Cut Line= 4
     1779429.713       439756.09     1779804.713        439637.6
     1779953.151       439655.83     1780224.635      439557.088
#Sta/Elev= 30
       0  969.79    88.5  962.98    98.3  960.17     118  948.84   137.6  939.77
   147.5  937.14   167.1   934.2   196.6  933.15   216.3  934.23   226.1  932.38
     236  929.44   245.8  927.82   265.5  926.32   403.2  926.37   443.1  925.09
   453.1  923.25   463.1  922.47   495.2  923.19   512.9  927.52   522.9  927.88
   542.8  926.08   562.8  926.87   582.7  926.52   612.6  927.95   622.5  929.35
   642.4  938.45   672.3  949.72   692.2  953.73   781.9  961.61   831.7  963.21
#Mann= 3 , 0 , 0
       0     .05       0   453.1    .045       0   495.2      .1       0
Bank Sta=453.1,495.2
XS Rating Curve= 0 ,0
Exp/Cntr=0.3,0.1

Chan Stop Cuts=-1
Use User Specified Reach Order=0
Composite Channel Slope=5